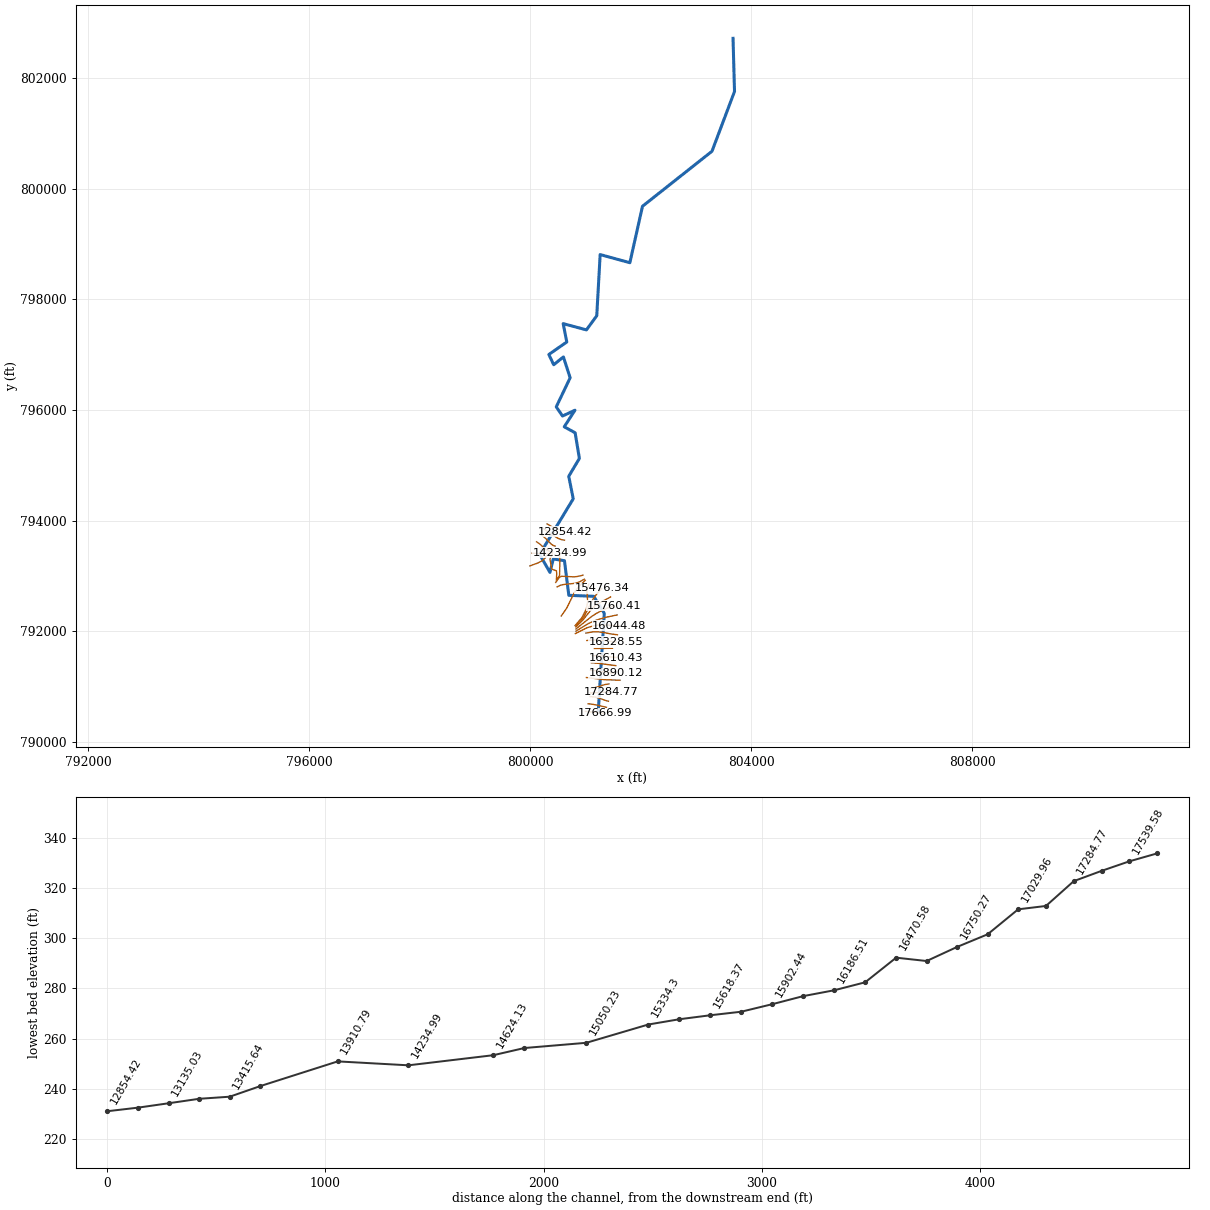
--- 17602_ras.prj (project) ---

Proj Title=17602
Current Plan=p01
Default Exp/Contr=0.3,0.1
English Units
Geom File=g01
Flow File=f01
Plan File=p01
Y Axis Title=Elevation
X Axis Title(PF)=Main Channel Distance
X Axis Title(XS)=Station
BEGIN DESCRIPTION:
RFD model 17602 exported to HEC-RAS
END DESCRIPTION:

--- 17602_ras.p01 (plan) ---

Plan Title=Plan 01
Program Version=4.10
Short Identifier=Plan 01
Geom File=g01
Flow File=f01
Subcritical Flow
Calc Critical at every XS
Secant Critical Depth

--- 17602_ras.f01 (steady flow) ---

Flow Title=Flow 01
Program Version=5.01
Number of Profiles= 6
Profile Names=10yr,25yr,50yr,100yr,100plus,500yr
River Rch & RM=17602,67,17666.99
 1224.74 1941.05 2608.62 3203.14 4676.58 6051.36
River Rch & RM=17602,67,17539.58
 1230.45 1950.29 2621.23  3218.8 4699.45  6077.5
River Rch & RM=17602,67,17412.18
 1232.88 1954.24 2626.62  3225.5 4709.23 6088.69
River Rch & RM=17602,67,17284.77
 1274.11 2020.96 2717.57 3338.47 4874.17  6276.5
River Rch & RM=17602,67,17157.37
 1280.03 2030.56 2730.67 3354.74 4897.92  6303.5
River Rch & RM=17602,67,17029.96
 1282.98 2035.34 2737.19 3362.85 4909.77 6316.98
River Rch & RM=17602,67,16890.12
 1301.73 2065.74 2778.68 3414.43 4985.07 6402.52
River Rch & RM=17602,67,16750.27
 1306.01 2072.67 2788.14 3426.19 5002.24 6422.01
River Rch & RM=17602,67,16610.43
 1312.17 2082.65 2801.76 3443.11 5026.94 6449.98
River Rch & RM=17602,67,16470.58
 1316.46 2089.59 2811.22 3454.87 5044.11 6469.41
River Rch & RM=17602,67,16328.55
 1319.11  2093.9 2817.11 3462.19  5054.8 6481.55
River Rch & RM=17602,67,16186.51
 1327.64 2107.84 2836.24  3486.1  5089.7 6521.52
River Rch & RM=17602,67,16044.48
 1333.28 2117.08 2848.93 3501.97 5112.87 6548.12
River Rch & RM=17602,67,15902.44
 1337.37 2123.78 2858.15 3513.49  5129.7 6567.44
River Rch & RM=17602,67,15760.41
  1338.9 2126.29  2861.6 3517.81 5136.01 6574.67
River Rch & RM=17602,67,15618.37
 1370.24 2177.91 2932.74 3607.03 5266.26 6724.77
River Rch & RM=17602,67,15476.34
 1377.32 2189.53 2948.73 3627.04 5295.47  6758.2
River Rch & RM=17602,67, 15334.3
 1389.52 2209.51 2976.18 3661.37  5345.6 6815.38
River Rch & RM=17602,67,15050.23
 1394.04 2216.93  2986.4 3674.17 5364.28 6836.77
River Rch & RM=17602,67,14766.16
 1435.03 2283.84 3078.12 3788.64 5531.41 7025.78
River Rch & RM=17602,67,14624.13
 1436.53  2286.3  3081.5 3792.88  5537.6 7032.83
River Rch & RM=17602,67,14234.99
 1444.13 2298.85 3098.83 3814.63 5569.36 7069.21
River Rch & RM=17602,67,13910.79
  1447.6 2304.57  3106.7  3824.5 5583.77 7085.61
River Rch & RM=17602,67,13555.94
 1511.57 2409.42 3250.83  4004.8    5847    7383
River Rch & RM=17602,67,13415.64
 1514.84 2414.87 3258.41 4014.37 5860.98 7399.12
River Rch & RM=17602,67,13275.33
 1515.53 2416.03 3260.03 4016.42 5863.97 7402.58
River Rch & RM=17602,67,13135.03
 1517.16 2418.75  3263.8  4021.2 5870.94 7410.63
River Rch & RM=17602,67,12994.72
  1520.4 2424.17 3271.36 4030.75 5884.89 7426.74
River Rch & RM=17602,67,12854.42
  1528.3 2437.36 3289.71 4053.94 5918.75 7465.79
River Rch & RM=17602,67,12634.99
  1533.4 2445.89 3301.56 4068.93 5940.63 7491.01
River Rch & RM=17602,67,12485.53
 1545.46 2466.03 3329.58 4104.33 5992.32  7550.5
River Rch & RM=17602,67,12336.08
 1547.54 2469.51 3334.41 4110.45 6001.25 7560.78
River Rch & RM=17602,67,12186.62
 1552.63 2478.01 3346.24  4125.4 6023.08 7585.88
River Rch & RM=17602,67,12037.16
  1556.1 2483.81  3354.3 4135.58 6037.95 7602.97
River Rch & RM=17602,67,11910.62
 1566.84  2501.8 3379.38 4167.34 6084.31 7656.44
River Rch & RM=17602,67,11738.24
 1568.88 2505.23 3384.16  4173.4 6093.16 7666.66
River Rch & RM=17602,67,11588.78
 1569.99 2507.11 3386.79 4176.74 6098.04 7672.34
River Rch & RM=17602,67,11439.32
 1572.66 2511.62 3393.11 4184.77 6109.76 7685.96
River Rch & RM=17602,67,11289.86
 1573.78  2513.5 3395.74 4188.11 6114.64 7691.63
River Rch & RM=17602,67, 11140.4
 1588.52 2538.35 3430.49 4232.24 6179.08 7766.33
River Rch & RM=17602,67,10990.94
 1590.74  2542.1 3435.74 4238.91 6188.81 7777.62
River Rch & RM=17602,67,10692.02
 1597.63 2553.73    3452 4259.58 6218.98 7812.59
River Rch & RM=17602,67,10394.73
  1592.3 2544.73 3439.41 4243.58 6195.63 7785.53
River Rch & RM=17602,67,9908.393
  1603.4 2563.46 3465.63 4276.89 6244.26 7841.88
River Rch & RM=17602,67,9665.223
 1608.29  2571.7 3477.15 4291.53 6265.64 7866.62
River Rch & RM=17602,67,9316.686
 1613.53 2580.58 3489.61  4307.4 6288.81 7893.58
River Rch & RM=17602,67,8933.743
 1615.26 2583.52 3493.75 4312.67  6296.5 7902.56
River Rch & RM=17602,67,8657.439
 1619.81 2591.25  3504.6 4326.51  6316.7  7926.1
River Rch & RM=17602,67,8174.049
 1622.19 2595.29 3510.28 4333.75 6327.28 7938.43
River Rch & RM=17602,67,7731.233
 1899.59 3057.68 4152.76 5145.09 7511.84 9270.22
River Rch & RM=17602,67,7465.903
 1900.64 3059.45 4155.26 5148.27 7516.48 9275.49
River Rch & RM=17602,67,7129.783
 1903.77 3064.77 4162.73  5157.8 7530.39 9291.29
River Rch & RM=17602,67,6925.508
 1911.96 3078.64 4182.19 5182.59 7566.58 9332.31
River Rch & RM=17602,67,6594.846
 1924.98 3100.68 4213.12 5221.98 7624.09 9397.39
River Rch & RM=17602,67,6396.947
 1931.55 3111.88 4228.89 5242.13 7653.51 9430.91
River Rch & RM=17602,67,6222.101
 1933.39 3115.02 4233.31 5247.78 7661.76 9440.33
River Rch & RM=17602,67,5950.436
 1936.86 3120.93 4241.65 5258.45 7677.34 9458.11
River Rch & RM=17602,67,5691.133
 1939.71 3125.81 4248.52 5267.24 7690.16 9472.74
River Rch & RM=17602,67,5429.616
 1940.53  3127.2 4250.49 5269.75 7693.83 9476.92
Boundary for River Rch & Prof#=17602,67,1
Up Type= 0
Dn Type= 2
Boundary for River Rch & Prof#=17602,67,2
Up Type= 0
Dn Type= 2
Boundary for River Rch & Prof#=17602,67,2
Up Type= 0
Dn Type= 2
Boundary for River Rch & Prof#=17602,67,2
Up Type= 0
Dn Type= 2
Boundary for River Rch & Prof#=17602,67,2
Up Type= 0
Dn Type= 2
Boundary for River Rch & Prof#=17602,67,2
Up Type= 0
Dn Type= 2

--- 17602_ras.g01 (geometry) ---

Geom Title=17602
Program Version=4.10

River Reach=17602,67
Reach XY= 30
 801228.15782422790523.819097293801338.510555269792321.335051945
801147.430251449792628.736906742800696.882766218792646.594394786
800617.730574818793273.183290769800415.217033654793304.520825104
  800355.7127893793061.046991466  800168.4674871 793387.01098249
800776.690430227794392.966951458800695.455923169794800.987292174
800888.066571922 795122.99848778 800811.13443354795587.311432715
800614.203908715 795696.07712838800807.882686227795996.450358746
800582.790353418795890.909891694 800469.51956275796057.233787277
800720.762234363796582.670769543800598.884701314796960.471117756
800423.414670439796819.059648082800335.146702289797004.923506836
800660.057845565797230.318464915 800594.64222482797562.909144453
801015.468299984797449.907363845 801202.07723689797704.702266889
801263.867088555   798812.758544801801.434688002798665.493063868
802030.067634792799687.049964635803287.461672873800682.026415253
803695.219065787801764.127476505803668.391655146802725.709465219

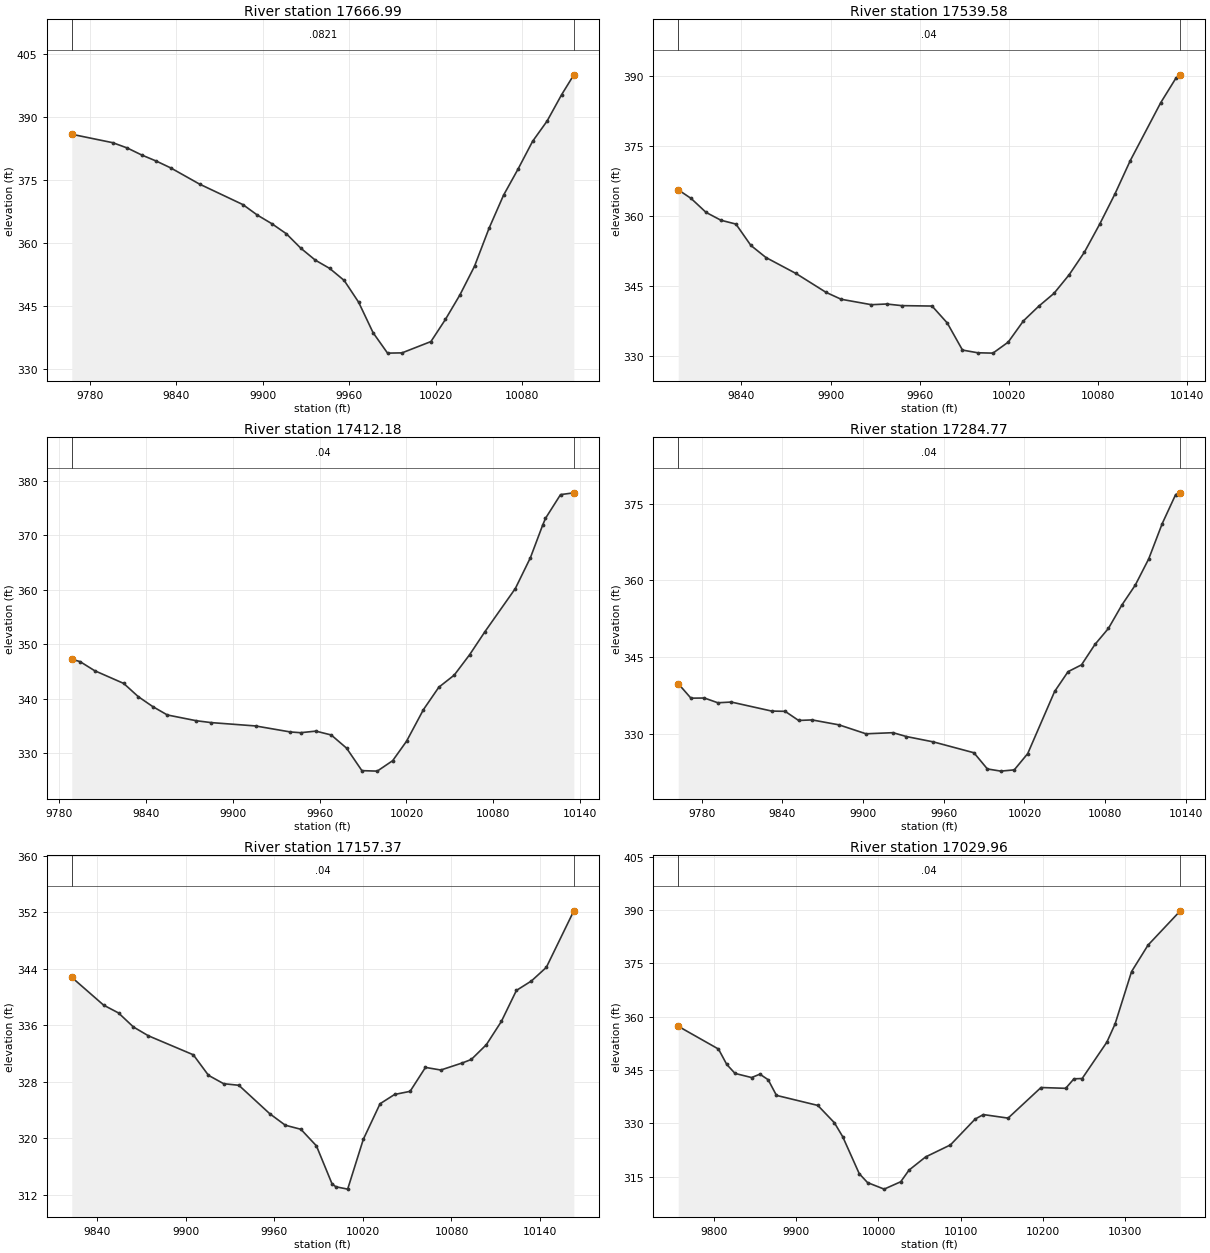
Type RM Length L Ch R = 1 ,17666.99,127.405500,127.405500,127.405500
XS GIS Cut Line= 6
800996.519962198790545.645028693801041.879885828790542.574000873
 801227.25669052790524.909032179801229.247759106790524.720230993
801243.383439899790523.326083738801343.429796121790510.257913145
#Sta/Elev= 30
 9767.32385.87379795.865383.85759805.888382.59969815.918380.92949825.963379.4906
9836.008377.86539856.099373.99249886.235369.1033 9896.28366.60039906.325364.5511
9916.371362.16339926.416358.71989936.461 355.8799946.507353.89059956.552351.0299
9966.597345.84079976.642338.57459986.688333.70639996.733333.767410016.83336.4663
10026.92341.7591   10037347.612210047.09354.410810057.17363.448410067.26371.3436
10077.34377.578410087.43384.185110097.51389.0199 10107.6395.3046 10116.1400.0394
#Mann= 3 , 0 , 0
 9767.32  0.0821       0 9767.32  0.0821       0 10116.1  0.0821       0
#XS Ineff= 2 , 0
       0                               0
Bank Sta=9767.32,10116.1
Exp/Cntr=0.3,0.1

Type RM Length L Ch R = 1 ,17539.58,127.405600,127.405600,127.405600
XS GIS Cut Line= 6
  801046.4124456790684.162318128801093.696543953790679.134516371
801151.329848677790670.104542846801208.977468604790658.960650241
801244.975096898790651.122319766801377.853256851790620.532749953
#Sta/Elev= 30
9797.557365.62459806.193363.77149816.249360.77839826.306359.08459836.362358.2666
9846.427353.68239856.549351.08729876.793347.65269897.037343.59869907.182342.1211
9927.552340.95379937.738341.10329947.923340.75559968.323340.66369978.557337.0276
9988.791331.21469999.026330.632710009.29 330.55710019.55332.916910029.82337.4889
10040.08340.624710050.34343.3812 10060.6347.397110070.81352.222410081.12358.2571
10091.38 364.73810101.64 371.86310122.17384.322110132.43389.615210135.35390.3062
#Mann= 3 , 0 , 0
9797.557    0.04       09797.557    0.04       010135.35    0.04       0
#XS Ineff= 2 , 0
       0                               0
Bank Sta=9797.557,10135.35
Exp/Cntr=0.3,0.1

Type RM Length L Ch R = 1 ,17412.18,127.405500,127.405500,127.405500
XS GIS Cut Line= 6
801079.274707507790814.573303947801162.037903369790806.314429657
801193.166609882790800.725865156801228.298112291790791.930395687
801359.924958228790744.654633375801413.944249297790729.387840118
#Sta/Elev= 30
9788.661347.29119794.392346.85419804.446345.19279824.554342.85089834.607 340.429
9844.661338.59649854.715337.06299874.854336.00029885.014335.66169915.669335.0475
9939.687333.94729946.791333.80869957.391334.09799967.992333.39179978.592330.9782
9989.192326.84799999.803326.756910010.46328.674810020.07332.250310031.74338.0502
10042.38342.159110053.02344.379510063.67348.127610074.31352.376110095.25360.2689
10105.66 365.91710114.09371.862710116.08 373.13710126.49377.498510135.69377.8258
#Mann= 3 , 0 , 0
9788.661    0.04       09788.661    0.04       010135.69    0.04       0
#XS Ineff= 2 , 0
       0                               0
Bank Sta=9788.661,10135.69
Exp/Cntr=0.3,0.1

Type RM Length L Ch R = 1 ,17284.77,127.405600,127.405600,127.405600
XS GIS Cut Line= 6
801085.551569811 790881.03419896801143.571284263790882.188390897
801207.126145225790885.680917853801298.724713907790893.436917972
801435.611144562790892.568056551801458.460309869790891.738757944
#Sta/Elev= 30
 9762.52339.7921 9771.97336.95269781.972336.98189791.974336.05249801.976336.1931
9831.997334.42939842.012334.37569852.027332.59119862.043 332.6979882.073331.7296
 9902.14  329.989922.211330.19869932.247  329.449952.319328.38989982.404326.2688
9992.405323.100110002.41322.673710012.41322.921110022.41326.106110042.41338.2619
10052.41342.140810062.41343.476710072.41347.470910082.41350.598210092.41355.1761
10102.41359.086910112.41 364.22810122.41371.109510132.42376.808410135.88377.1402
#Mann= 3 , 0 , 0
 9762.52    0.04       0 9762.52    0.04       010135.88    0.04       0
#XS Ineff= 2 , 0
       0                               0
Bank Sta=9762.52,10135.88
Exp/Cntr=0.3,0.1

Type RM Length L Ch R = 1 ,17157.37,127.405500,127.405500,127.405500
XS GIS Cut Line= 6
801093.537124752790965.587133672 801173.92010159790977.129510728
801208.934322768790985.583180781801308.846030084791019.645499493
801349.092182358791031.149056082801423.534758616791043.307382313
#Sta/Elev= 30
9822.748342.81079844.346338.8702 9854.41337.76849864.509335.78069874.653334.5309
9905.098 331.8389915.386328.92739925.673327.7415 9935.96327.51839956.923323.4836
9967.451321.8586 9977.98321.28529988.508318.93869999.038313.585710001.62313.1437
10009.68312.808110020.28319.866110031.63324.9053 10041.5326.219610051.98326.6615
10062.38330.050910072.78329.680610087.43330.690710093.45331.177410103.64333.2707
10113.82336.565610124.01340.9576 10134.2342.299810144.28344.223110162.92352.2329
#Mann= 3 , 0 , 0
9822.748    0.04       09822.748    0.04       010162.92    0.04       0
#XS Ineff= 2 , 0
       0                               0
Bank Sta=9822.748,10162.92
Exp/Cntr=0.3,0.1

Type RM Length L Ch R = 1 ,17029.96,139.845000,139.845000,139.845000
XS GIS Cut Line= 4
801016.405641675  791159.1077521801227.994037181791134.541309178
 801341.31666097791120.276922956801624.226987481791109.974866241
#Sta/Elev= 30
 9756.57357.3257 9805.49  350.919815.557346.57879825.625344.04889845.759342.8873
9855.826343.84039865.893342.27229875.961337.86779926.296335.03599946.431330.1501
9956.498326.23449976.641315.80819986.719313.308610006.88311.471310027.04313.5494
10037.11316.829210057.27320.536510087.48323.9259 10117.5331.203310127.51332.4608
10157.53 331.46510197.55340.077810227.57339.854210237.58342.529610247.59342.6178
10277.61352.857410287.61357.992710307.63372.721210327.64380.175710366.89389.8297
#Mann= 3 , 0 , 0
 9756.57    0.04       0 9756.57    0.04       010366.89    0.04       0
#XS Ineff= 2 , 0
       0                               0
Bank Sta=9756.57,10366.89
Exp/Cntr=0.3,0.1

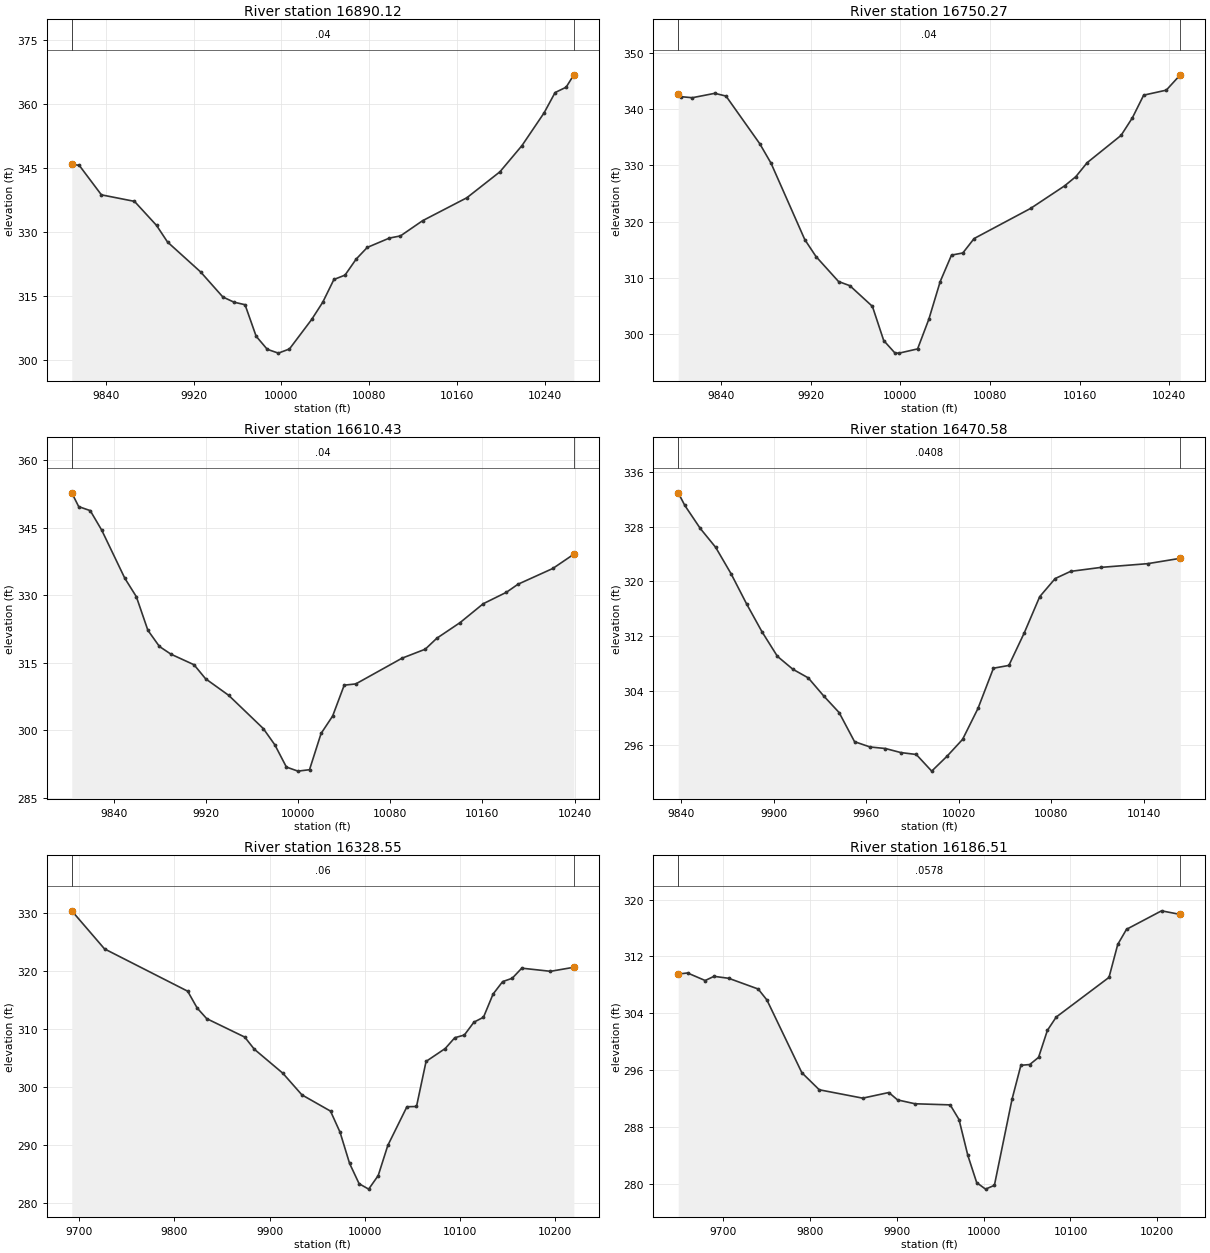
Type RM Length L Ch R = 1 ,16890.12,139.845000,139.845000,139.845000
XS GIS Cut Line= 6
801088.117323487791291.814660802801198.665977775791281.199698403
801276.736140083791269.307461034 801364.48479932791255.231737842
801446.100209444791244.617650117801542.006805479791234.913975809
#Sta/Elev= 30
9808.966 345.9569815.866345.60289835.962338.70939866.106 337.1789886.202331.5377
 9896.25327.62679926.436320.59689946.667314.72289956.782 313.5079966.898 312.905
9977.013305.50279987.128302.43999997.244301.539610007.37302.516810027.63309.4486
10037.75313.507410047.88318.832510058.01319.858310068.14323.610310078.26326.3547
10098.47328.556910108.56329.064710128.73332.636610169.06338.022510199.22344.1216
10219.32350.282610239.42357.943310249.48 362.72610259.53363.978810266.57366.8872
#Mann= 3 , 0 , 0
9808.966    0.04       09808.966    0.04       010266.57    0.04       0
#XS Ineff= 2 , 0
       0                               0
Bank Sta=9808.966,10266.57
Exp/Cntr=0.3,0.1

Type RM Length L Ch R = 1 ,16750.27,139.845100,139.845100,139.845100
XS GIS Cut Line= 6
801102.479410685791426.755713019801113.492251108  791426.4314393
801233.925544975791415.444807929801300.675414823791407.110919454
801542.955880812791374.475328952801547.417119559791373.959047897
#Sta/Elev= 30
9801.781342.78129804.303342.27299814.313342.08769834.396342.87139844.437342.3808
9874.562333.87829884.603330.40989914.728316.78239924.769313.75019944.892309.2938
 9954.97308.55429975.125304.85739985.202298.7662 9995.28296.5321    9999296.5211
10015.45297.275610025.54302.604610035.63309.292210045.72314.009410055.82314.3893
10065.91316.966310116.36322.342810146.63326.357310156.72328.009110166.81330.4994
10197.08335.367310207.17338.500910217.26342.545210237.44343.437910249.96346.1713
#Mann= 3 , 0 , 0
9801.781    0.04       09801.781    0.04       010249.96    0.04       0
#XS Ineff= 2 , 0
       0                               0
Bank Sta=9801.781,10249.96
Exp/Cntr=0.3,0.1

Type RM Length L Ch R = 1 ,16610.43,139.845000,139.845000,139.845000
XS GIS Cut Line= 6
801118.979525754791556.006614388801160.416872176 791555.47844751
801280.630666789 791548.76485708801316.025015706791546.121942461
801402.420915001791538.441345567801553.151697138791521.337691896
#Sta/Elev= 30
9803.665352.78329809.686349.71529819.687348.82729829.688344.47459849.696333.7965
9859.712329.69399869.727322.22249879.743318.62529889.759316.9111 9909.79314.5597
9919.805 311.4469939.836307.76719969.889300.37759979.916296.75829989.944291.8169
9999.972290.911910010.01291.228210020.05299.286710030.09303.164710040.13310.0241
10050.17310.300410090.33316.023710110.46 318.01910120.52320.459910140.65323.9237
10160.78328.126610180.91330.673610190.97332.463710221.17335.963810239.43339.1372
#Mann= 3 , 0 , 0
9803.665    0.04       09803.665    0.04       010239.43    0.04       0
#XS Ineff= 2 , 0
       0                               0
Bank Sta=9803.665,10239.43
Exp/Cntr=0.3,0.1

Type RM Length L Ch R = 1 ,16470.58,142.034700,142.034700,142.034700
XS GIS Cut Line= 4
801160.728127658791684.064693555801311.388884246791685.638761163
801351.190308034 791686.31336157801486.110388547 791688.11229597
#Sta/Elev= 30
9838.239332.97019842.511331.12259852.511327.75959862.512324.98869872.512321.1152
9882.513316.72789892.513312.63969902.514309.04179912.515307.15389922.515305.8857
9932.516303.24539942.516300.81059952.517296.54979962.517295.77679972.518295.5494
9982.518294.95549992.519294.677410002.52  292.2410012.52294.436510022.52296.8815
10032.52301.418410042.53307.302910052.53307.708910062.53312.484710072.53317.7751
10082.53320.421110092.53321.474310112.53 322.06510142.53322.603510163.65323.3878
#Mann= 3 , 0 , 0
9838.239  0.0408       09838.239  0.0408       010163.65  0.0408       0
#XS Ineff= 2 , 0
       0                               0
Bank Sta=9838.239,10163.65
Exp/Cntr=0.3,0.1

Type RM Length L Ch R = 1 ,16328.55,142.034700,142.034700,142.034700
XS GIS Cut Line= 6
801023.523760473791828.505276918801057.624168424791833.241388723
801143.916804958791837.550396675801224.983602724791835.604724348
801341.449264656 791826.63038401801549.402791738791802.658024406
#Sta/Elev= 30
9691.972330.3313  9726.4323.78299813.883316.50059823.886313.59949833.889311.7791
  9873.9308.60529883.903306.52819913.963302.38649934.021298.66389964.107295.8684
9974.135292.23579984.164286.86939994.192283.372810004.23282.443710014.28284.7796
10024.34289.954210044.47296.620610054.54 296.66310064.61304.419610084.74306.6374
10094.81 308.49710104.87308.960810114.94311.1731   10125312.022610135.07316.0055
10145.14318.1509 10155.2318.727710165.27320.464110195.47319.923910220.03320.6198
#Mann= 3 , 0 , 0
9691.972    0.06       09691.972    0.06       010220.03    0.06       0
#XS Ineff= 2 , 0
       0                               0
Bank Sta=9691.972,10220.03
Exp/Cntr=0.3,0.1

Type RM Length L Ch R = 1 ,16186.51,142.034700,142.034700,142.034700
XS GIS Cut Line= 6
801004.901017812791962.250428579801128.001481333 791984.81711239
801226.037768673791986.064145612801318.946294133791974.373365131
801464.421871044791947.051889248801576.449015552791932.817976492
#Sta/Elev= 30
9648.412309.51559659.134309.66999679.409308.60889689.612309.19669706.539308.9205
9740.455307.41459750.533305.86749790.741295.64269810.774293.24579860.785292.0674
9890.875292.86099900.921291.82299921.022 291.2789961.513291.12319971.675289.0641
9981.861284.00919992.048280.185110002.24279.276210012.41279.810510032.75291.9293
10042.92296.688710053.09296.793510063.26297.802410073.43301.6005 10083.6303.4726
10144.35309.047110154.43313.686610164.51315.807210204.83318.407710226.46 317.898
#Mann= 3 , 0 , 0
9648.412  0.0578       09648.412  0.0578       010226.46  0.0578       0
#XS Ineff= 2 , 0
       0                               0
Bank Sta=9648.412,10226.46
Exp/Cntr=0.3,0.1

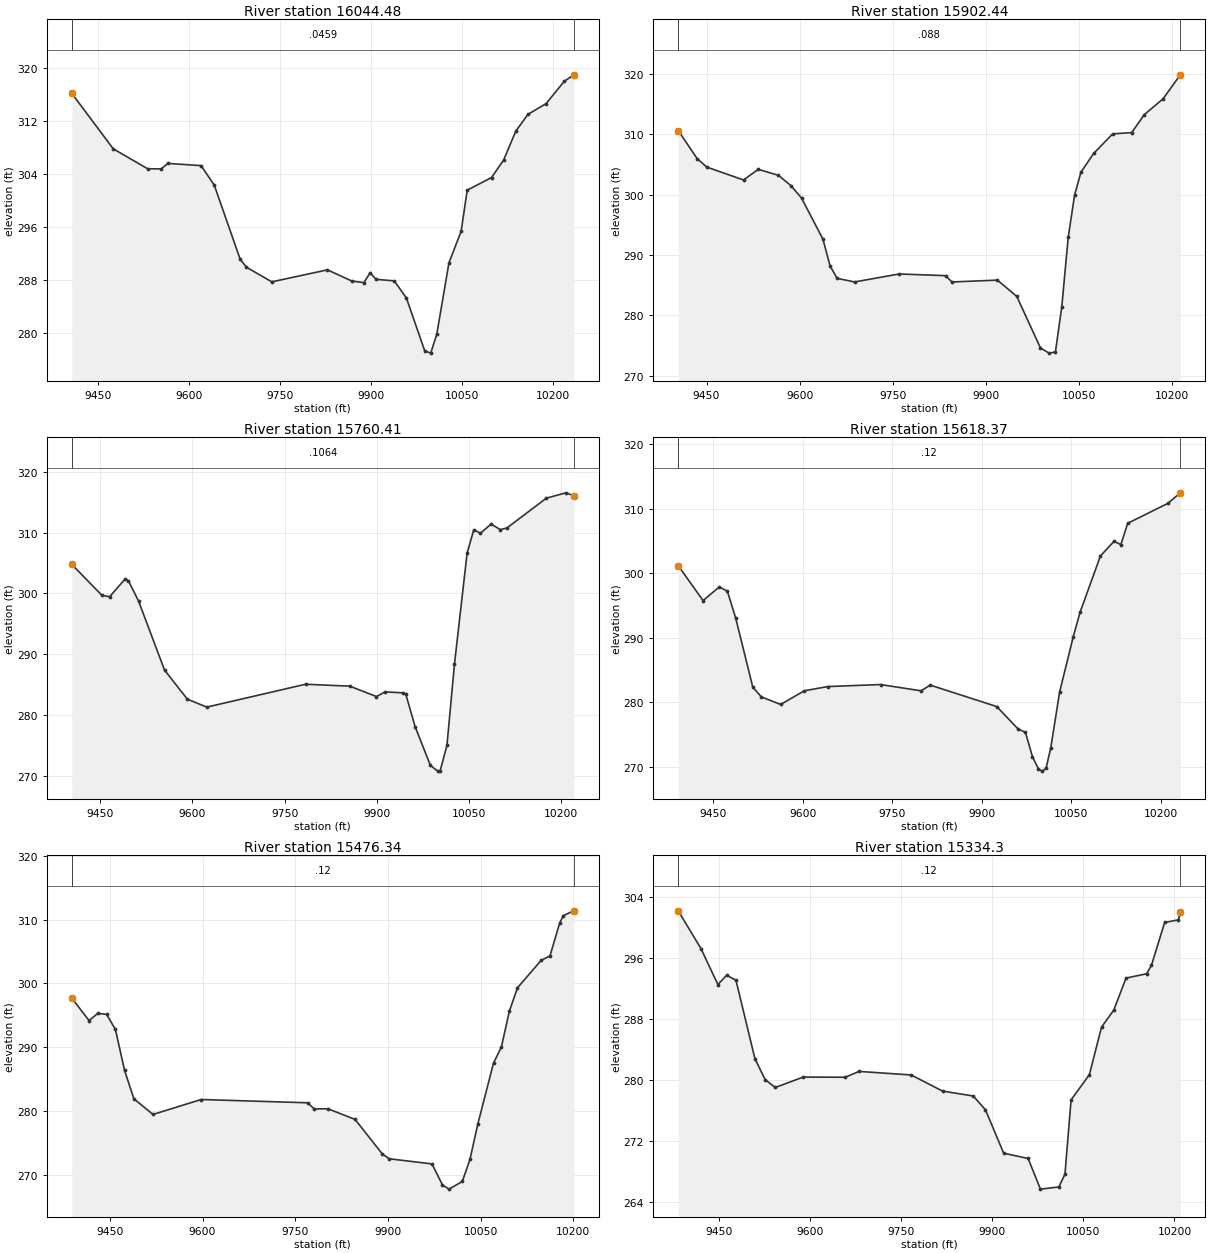
Type RM Length L Ch R = 1 ,16044.48,142.034800,142.034800,142.034800
XS GIS Cut Line= 6
800814.897633354791954.121188776801020.438003305792057.385205466
801151.800539821792097.591087245801207.103245766792106.531594342
801304.399403902 792111.48829115801610.673750644792097.524514097
#Sta/Elev= 30
9406.014316.19999474.428 307.8169531.077304.80799553.447304.78619564.534305.6147
9619.275305.2788 9641.06 302.3139683.589291.15399694.085289.92339735.873287.7221
9827.612289.53439867.764287.84069887.815287.60349897.816289.07679907.817288.1005
9937.834287.86739957.862285.25999987.905277.31439997.919276.950410007.94279.8453
10027.98290.611910048.03295.351910058.05301.569710098.13303.478410118.14306.1307
10138.16 310.49210158.17313.014810188.18314.659510218.19318.032410233.87318.9987
#Mann= 3 , 0 , 0
9406.014  0.0459       09406.014  0.0459       010233.87  0.0459       0
#XS Ineff= 2 , 0
       0                               0
Bank Sta=9406.014,10233.87
Exp/Cntr=0.3,0.1

Type RM Length L Ch R = 1 ,15902.44,142.034700,142.034700,142.034700
XS GIS Cut Line= 6
800826.158003027791998.690365206  801052.2529413792136.373581044
801147.136189922792180.233855774801250.760445907792216.124032577
801363.857766768792248.438956173801572.237669893792291.612737919
#Sta/Elev= 30
9404.337310.61119434.755305.97619450.353304.55919509.588302.42399533.282  304.18
9565.729303.20419585.855301.5066 9603.15299.42689637.719 292.5999649.242288.1529
9660.765286.11899688.702285.53049760.484286.85019835.306286.5713 9845.81285.5245
9918.989285.83329950.191283.1391  9988.4274.601110002.18273.737910012.51 273.921
10022.84281.448810033.17292.930310043.44299.925210053.69303.7097 10074.2 306.823
10104.93310.061210135.49310.265410155.87313.242710186.32315.889910213.91319.8415
#Mann= 3 , 0 , 0
9404.337   0.088       09404.337   0.088       010213.91   0.088       0
#XS Ineff= 2 , 0
       0                               0
Bank Sta=9404.337,10213.91
Exp/Cntr=0.3,0.1

Type RM Length L Ch R = 1 ,15760.41,142.034700,142.034700,142.034700
XS GIS Cut Line= 6
800826.205920811792038.620625371801057.157171843792222.774805076
801116.463835125792267.988695864  801187.7073196792315.062504043
801336.039773274792391.775855852801517.185949804792461.584923617
#Sta/Elev= 30
9403.727304.78749452.749299.68919465.386 299.4639490.659 302.3979495.947 302.067
9512.304298.7592 9554.58287.38929591.699282.59359623.402281.28749783.939  285.05
9855.853284.73669899.284283.02449913.342283.79599942.458283.63199947.123283.3709
9962.158 278.0749987.067271.6839    9999270.747510002.94270.805310013.98275.0009
10026.16288.334310046.75306.633310057.61310.480510068.47309.910310085.73311.4179
10100.91310.498510111.62310.787510175.73315.687110207.47316.561910220.36316.0811
#Mann= 3 , 0 , 0
9403.727  0.1064       09403.727  0.1064       010220.36  0.1064       0
#XS Ineff= 2 , 0
       09926.347                       0
Bank Sta=9403.727,10220.36
Exp/Cntr=0.3,0.1

Type RM Length L Ch R = 1 ,15618.37,142.034700,142.034700,142.034700
XS GIS Cut Line= 6
 800824.24698883792075.548747188800947.578842226 792195.08832909
801092.299932616792375.391586048801160.276890246792448.172354428
801234.767893069792500.009568722801453.373384673792617.659289553
#Sta/Elev= 30
 9391.13301.1762  9432.8295.7676  9459.9297.8803 9473.45297.23469487.395293.0928
9516.141282.35339530.514280.84739562.843279.6668 9602.45 281.7869641.811282.4438
9730.434 282.756 9798.39281.78359813.791282.66539925.194279.34779961.519275.8268
9973.294275.36519985.061271.59349995.148269.6815   10001269.337610007.88269.7557
10015.94272.996210030.69281.599710053.51 290.15310064.92293.943110099.15302.6929
10121.97304.959510133.38304.445410144.79307.742710212.45310.847510233.07312.4691
#Mann= 3 , 0 , 0
 9391.13    0.12       0 9391.13    0.12       010233.07    0.12       0
#XS Ineff= 2 , 0
       09751.644                       0
Bank Sta=9391.13,10233.07
Exp/Cntr=0.3,0.1

Type RM Length L Ch R = 1 ,15476.34,142.034700,142.034700,142.034700
XS GIS Cut Line= 6
 800835.36316028792106.432647805800914.735587953792189.989928078
800980.041381549792276.641824388801133.873142161792577.056950446
801221.018312447792695.345569393801292.611365703792770.729229174
#Sta/Elev= 30
9388.277297.71279416.221294.18259430.452295.31169444.682295.15859458.913292.7885
9473.778286.3556 9488.87 281.9069519.803279.46189597.757281.80419769.885281.2889
9780.898280.33229802.924280.35239846.976278.67659891.027273.26239902.281272.5074
9971.443271.70549988.323  268.41    9999267.751610020.45268.948910032.92272.4267
10045.44277.897110070.99287.510710083.77290.047710096.54295.613110109.81299.3222
10148.13303.621210162.49304.3423   10178309.455510184.06310.636710201.04311.3869
#Mann= 3 , 0 , 0
9388.277    0.12       09388.277    0.12       010201.04    0.12       0
#XS Ineff= 2 , 0
       09714.596                       0
Bank Sta=9388.277,10201.04
Exp/Cntr=0.3,0.1

Type RM Length L Ch R = 1 , 15334.3,284.069500,284.069500,284.069500
XS GIS Cut Line= 6
800809.499430745792098.218306354800936.233861317792246.092027301
801013.708961641792400.313191374801038.068916094792529.391499234
801022.317622109792741.394884116801058.819653007 792847.59382904
#Sta/Elev= 30
9383.512302.16659420.877297.21849448.762292.49389463.176293.71749478.516293.0586
 9509.71282.77379526.414280.02989543.118 278.9919589.169280.35559658.528280.3352
9681.093281.09859766.871280.63229818.554 278.5159868.991277.87559889.041276.0705
9919.069270.3664 9959.31269.67829979.538265.655810009.84265.941610019.92267.6208
10029.99277.365910060.08280.6672 10080.1 286.90710100.19 289.13910120.48293.3449
10154.38293.909610162.25295.023810183.97300.6403 10206.6300.979210209.74301.9528
#Mann= 3 , 0 , 0
9383.512    0.12       09383.512    0.12       010209.74    0.12       0
#XS Ineff= 2 , 0
       09732.075                       0
Bank Sta=9383.512,10209.74
Exp/Cntr=0.3,0.1

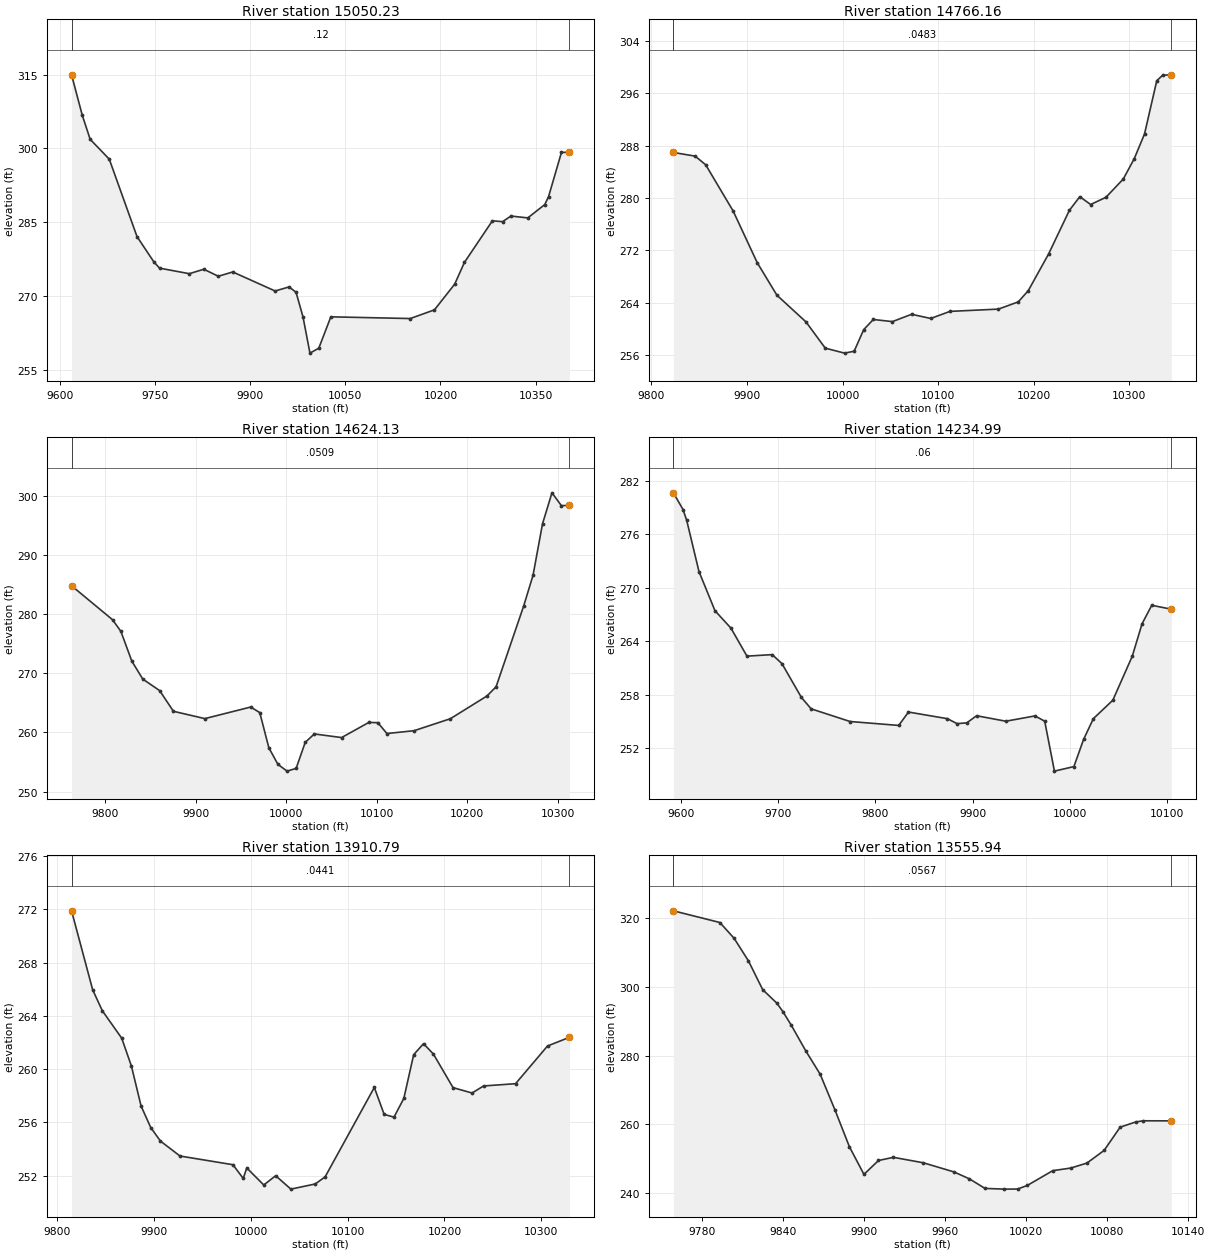
Type RM Length L Ch R = 1 ,15050.23,284.069400,284.069400,284.069400
XS GIS Cut Line= 6
800559.282422531792271.973879393800658.774758359 792415.38824584
800792.941238145792687.425326563800823.558706312792737.055456159
 800882.12959583792810.442038846800994.592172682792916.373129803
#Sta/Elev= 30
 9618.38314.97399635.232306.77099647.705 301.8659677.848297.82339721.566282.0829
9748.341276.90269757.199275.66469804.062274.53939826.926275.4429 9849.79 274.015
9872.547274.88959939.387271.01979961.352 271.848 9972.33270.76339983.307265.7497
9994.284258.386710008.23259.398610027.21265.768310152.45265.417710190.57 267.188
10222.48272.410710237.85 276.83810281.93285.290810298.03285.116710311.09286.2613
10337.72285.882410364.53288.592310370.52290.216610390.83299.201710403.44299.2203
#Mann= 3 , 0 , 0
 9618.38    0.12       0 9618.38    0.12       010403.44    0.12       0
#XS Ineff= 2 , 0
       0                               0
Bank Sta=9618.38,10403.44
Exp/Cntr=0.3,0.1

Type RM Length L Ch R = 1 ,14766.16,142.034700,142.034700,142.034700
XS GIS Cut Line= 6
800485.234102025792798.719111149800541.048568638792826.557074163
800593.130870906792841.011230388800822.086917414792865.021819973
800895.606954814792892.341396702800977.921035232792939.771217443
#Sta/Elev= 30
9823.188286.9757 9845.93286.41739856.947285.08899885.647278.02799910.819 270.132
9931.399265.15949961.807261.08239981.982257.067310002.14256.309210012.17256.6001
10022.18259.9024 10032.2261.449810052.22261.127610072.24262.245510092.28261.6048
10112.37262.688610163.04263.037910183.76264.140110194.22265.850510215.51271.4654
10237.26278.139810248.14280.221510259.47279.022310275.46280.126410293.56 282.912
 10305.1286.037310315.82289.807610328.63 297.94810334.79 298.78610343.84298.8445
#Mann= 3 , 0 , 0
9823.188  0.0483       09823.188  0.0483       010343.84  0.0483       0
#XS Ineff= 2 , 0
       0                               0
Bank Sta=9823.188,10343.84
Exp/Cntr=0.3,0.1

Type RM Length L Ch R = 1 ,14624.13,389.138100,389.138100,389.138100
XS GIS Cut Line= 6
 800459.64225352792879.839419903800525.506691703792971.962667766
800564.201028964792991.376673526800786.724528561792981.440679971
800847.320200335792986.326305405800953.509325969793011.470512621
#Sta/Elev= 30
9762.753284.82369808.031279.07999817.265277.10969829.336272.08379841.407269.0452
 9860.16267.07859875.373263.58119910.117262.3446  9960.8264.30379970.813263.3628
9980.841257.40939990.898254.597610000.95253.457710011.01253.922410021.06258.3263
10031.11259.748710061.27259.136910091.35261.696610101.35261.654910111.35259.8188
10141.35260.297510181.48262.323210221.86266.160910232.03267.730310262.56281.4059
10272.93286.621410283.38295.319610293.82300.550710304.27298.377910313.15298.4432
#Mann= 3 , 0 , 0
9762.753  0.0509       09762.753  0.0509       010313.15  0.0509       0
#XS Ineff= 2 , 0
       0                               0
Bank Sta=9762.753,10313.15
Exp/Cntr=0.3,0.1

Type RM Length L Ch R = 1 ,14234.99,324.204400,324.204400,324.204400
XS GIS Cut Line= 4
800468.997856084792924.178396509800529.989105493793003.663253292
800533.895355493793254.965336636800532.593272179793415.121586621
#Sta/Elev= 30
9592.491280.6622 9602.35278.78669606.131277.57439618.736271.83199635.204 267.432
 9651.63265.47649668.057 262.3389694.016262.50949704.017261.4979 9724.02257.7035
9734.021256.42459774.026255.00369824.032254.56329834.033256.06579874.038255.3203
9884.039254.7627 9894.04254.85439904.042255.65319934.045255.03649964.047255.6302
9974.047255.04019984.048249.436510004.05249.945210014.05 253.00810024.05255.3237
10044.05257.393310064.05262.333710074.05265.956610084.05268.044110104.17267.6047
#Mann= 3 , 0 , 0
9592.491    0.06       09592.491    0.06       010104.17    0.06       0
#XS Ineff= 2 , 0
       0                               0
Bank Sta=9592.491,10104.17
Exp/Cntr=0.3,0.1

Type RM Length L Ch R = 1 ,13910.79,354.846600,354.846600,354.846600
XS GIS Cut Line= 6
800473.284236282792953.221941143800478.079787999793045.136681497
800472.408676475793090.479648471800388.562823474793120.266990975
800354.317800194793302.674156085800397.176605523793395.590336636
#Sta/Elev= 30
9814.596271.88939836.404265.96259846.417264.38349866.444262.32789876.458260.2343
9886.472257.22959896.485255.61269906.499254.59999926.654253.48029981.419252.8261
9992.031251.79589995.707 252.58410013.26251.306210025.58251.998910041.31250.9938
10066.48251.381210076.65251.911710127.53 258.628 10137.7256.604710147.87256.3997
10158.05257.806810168.22261.0918 10178.4 261.91310188.57261.138910208.92258.6132
10228.53258.210710240.48258.740810273.52258.909710306.55261.740110329.23262.3934
#Mann= 3 , 0 , 0
9814.596  0.0441       09814.596  0.0441       010329.23  0.0441       0
#XS Ineff= 2 , 0
       0                               0
Bank Sta=9814.596,10329.23
Exp/Cntr=0.3,0.1

Type RM Length L Ch R = 1 ,13555.94,140.304600,140.304600,140.304600
XS GIS Cut Line= 6
799992.493506726793178.489734924800134.380821232793230.617503214
800204.025474642793266.517164173800231.554192872793285.515376634
800268.173492958793320.824004787800293.267153229793369.260598431
#Sta/Elev= 30
9758.722 322.2189793.106318.81769803.683314.2066 9814.26307.66199824.838299.2612
9835.415295.30049840.075292.70169846.081288.85589856.831281.37589867.375274.6655
9878.332264.26679889.083 253.4989899.833245.46479910.602 249.5159921.647250.4358
9943.793 248.8489966.443246.19339977.948244.16769989.489241.3845 10003.8 241.175
10013.71241.204810020.91242.267410039.71246.558710053.03247.310110065.01248.7669
10077.72252.4513 10089.6259.220410101.06260.722710106.62261.075610127.49261.0534
#Mann= 3 , 0 , 0
9758.722  0.0567       09758.722  0.0567       010127.49  0.0567       0
#XS Ineff= 2 , 0
       09956.166                       0
Bank Sta=9758.722,10127.49
Exp/Cntr=0.3,0.1

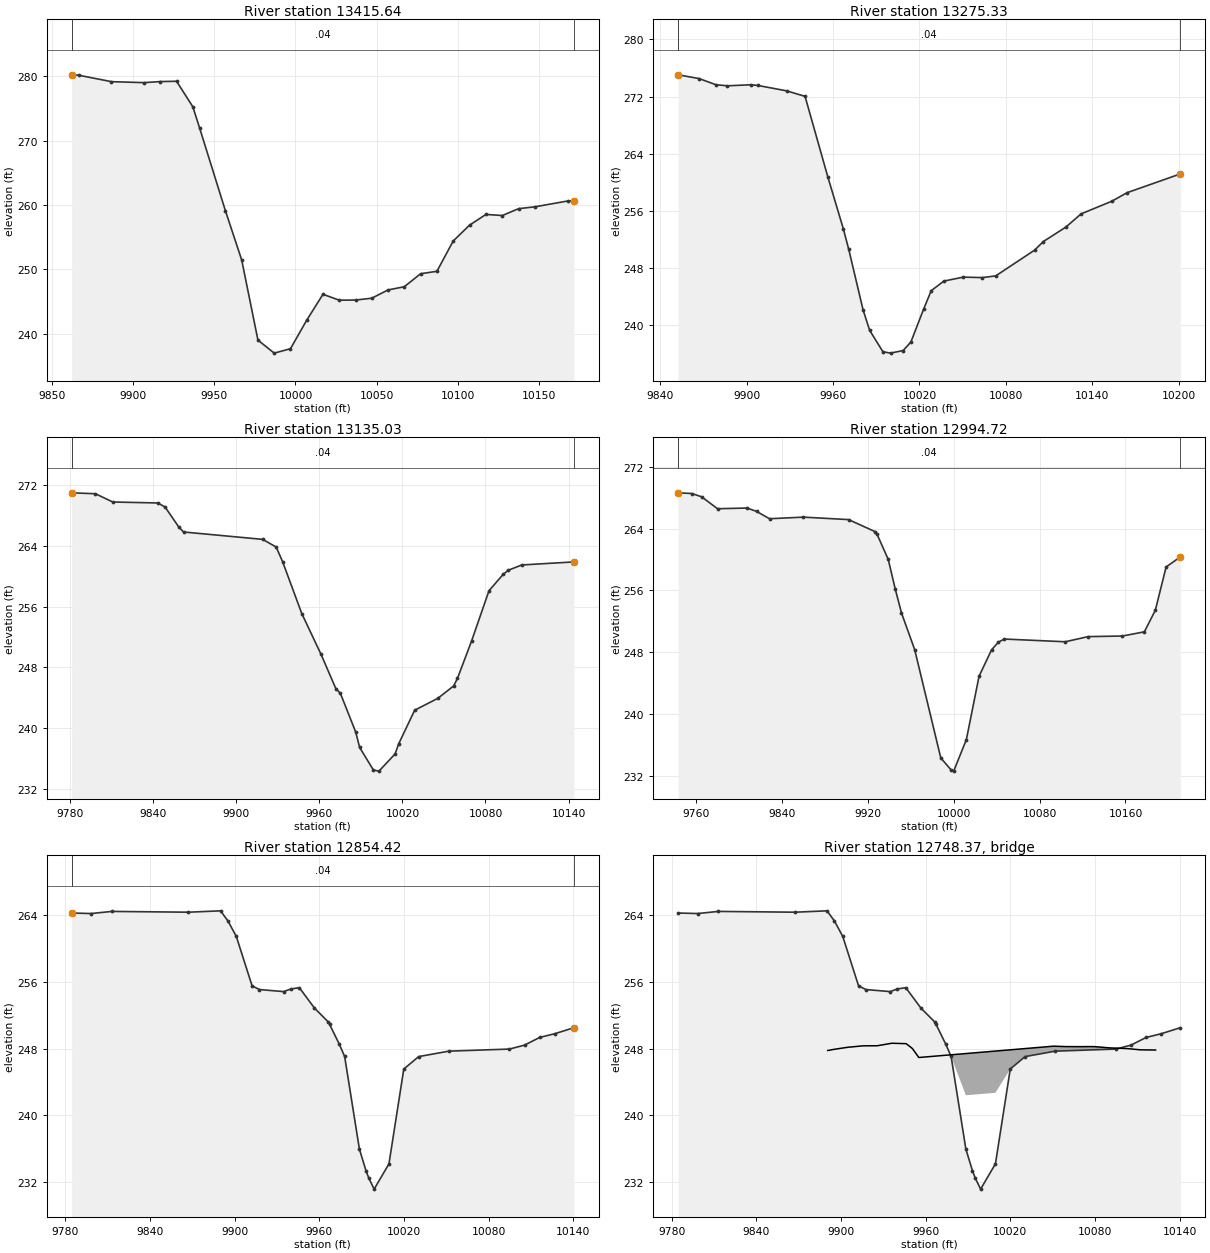
Type RM Length L Ch R = 1 ,13415.64,140.304500,140.304500,140.304500
XS GIS Cut Line= 6
800030.546170563793409.071676746800140.954794824793403.353280604
800167.081280649 793403.24711059800223.011874706793404.276663408
800264.490470886  793407.4091288800338.713873237793398.914847761
#Sta/Elev= 30
9862.317280.21589866.776280.14859886.803279.1535 9906.83279.00149916.844279.1675
9926.857279.2154 9936.87275.24359941.036271.94719956.897259.08879966.911251.4423
9976.919238.97469986.919236.95189996.919237.638510006.92242.072210016.92246.0971
10026.92245.182510036.93245.202410046.93245.488910056.93246.773210066.96247.2744
10076.99249.295410087.02249.673210097.05254.388810107.11256.850810117.18258.5152
10127.25258.342610137.31259.412110147.38259.701110167.51260.605310171.24260.6207
#Mann= 3 , 0 , 0
9862.317    0.04       09862.317    0.04       010171.24    0.04       0
#XS Ineff= 2 , 0
       0                               0
Bank Sta=9862.317,10171.24
Exp/Cntr=0.3,0.1

Type RM Length L Ch R = 1 ,13275.33,140.304600,140.304600,140.304600
XS GIS Cut Line= 6
 800112.61950022793615.289538667800172.044075549793575.594614074
800258.231909633793495.540878028800294.235191047793466.472392857
800310.351161659793457.955791205800399.707928389793425.189209983
#Sta/Elev= 30
9852.284275.04619866.794 274.5279878.515 273.6639886.499273.50989902.771273.6552
9907.743273.55669927.626272.80799940.487272.03579956.239260.82139967.053253.5316
9970.849250.63049980.826242.15639985.392239.3021  9994.6 236.3139999.903236.1186
10008.64236.483710014.03237.6708 10022.8242.230810028.16244.850910036.95246.1959
10050.47246.750610063.69246.684610072.96 246.91910100.03250.528810106.08251.7275
10121.68253.741710132.33255.597310153.64257.364610164.29258.561810201.25261.1857
#Mann= 3 , 0 , 0
9852.284    0.04       09852.284    0.04       010201.25    0.04       0
#XS Ineff= 2 , 0
       0                               0
Bank Sta=9852.284,10201.25
Exp/Cntr=0.3,0.1

Type RM Length L Ch R = 1 ,13135.03,140.304500,140.304500,140.304500
XS GIS Cut Line= 6
800171.070711399793762.154346533800220.072245925793725.871617906
800281.728291472793671.681034704800377.322908671793574.592265003
800406.147495608 793552.71941997800450.296099188793536.695525913
#Sta/Elev= 30
9780.992270.98069798.184270.8606 9810.67269.77249843.293269.64539848.533269.1012
9858.441 266.4699861.847265.82469919.031264.8519 9928.76263.84459933.363261.9386
9947.289255.07579961.215249.70389971.865245.20559975.141244.59139986.234239.4771
9989.067237.4573    9999234.487110003.02234.338710014.72236.6126 10017.2237.9003
10028.83242.358810045.56243.921110057.04245.560510059.74 246.54810069.95251.4702
10082.51 258.08210092.73260.2398 10096.5260.791210106.27261.484410143.83261.8838
#Mann= 3 , 0 , 0
9780.992    0.04       09780.992    0.04       010143.83    0.04       0
#XS Ineff= 2 , 0
       0                               0
Bank Sta=9780.992,10143.83
Exp/Cntr=0.3,0.1

Type RM Length L Ch R = 1 ,12994.72,140.304600,140.304600,140.304600
XS GIS Cut Line= 6
800214.211801796793870.550867778 800403.34754185793738.339733655
 800487.22531577793685.892160109800517.003354297 793670.95961506
800562.781469112793654.229042766800618.137911152793644.609226748
#Sta/Elev= 30
9743.029268.63759755.773268.54969764.919268.12669779.764266.57929807.282266.6659
9816.099266.2365 9828.21265.28349859.832265.48999901.914265.17079926.568263.6146
9928.242263.34029938.894260.00859945.344256.21619951.221253.08579963.548248.3227
 9987.86234.3056 9997.82232.6964 9999.88232.597410011.71236.681710023.54244.8874
 10035.2 248.30810041.53249.296710047.08249.702610103.86249.350110125.26 250.016
10157.12250.0933 10177.6250.636510187.83  253.4310197.89259.039110211.11 260.335
#Mann= 3 , 0 , 0
9743.029    0.04       09743.029    0.04       010211.11    0.04       0
#XS Ineff= 2 , 0
       0                               0
Bank Sta=9743.029,10211.11
Exp/Cntr=0.3,0.1

Type RM Length L Ch R = 1 ,12854.42,219.423900,219.423900,219.423900
XS GIS Cut Line= 6
800303.064653356793939.177482586800385.527624374793892.120098525
800443.328765543793863.131312656800471.360713058  793852.1059541
 800526.42121789793834.760809816800627.583584646793795.404886276
#Sta/Elev= 30
9784.449264.27189798.191264.20759813.054 264.4639867.273264.36889889.991264.5334
9895.277263.31379901.178261.46279912.366255.53969917.583255.0966 9934.74254.8515
9939.889255.16839945.853255.32259956.599252.87079966.273251.23069967.345250.9078
 9974.18248.55069977.984247.07359988.437235.97649993.082  233.399995.082232.5057
9998.893231.1731 10009.4234.203710019.91245.564810030.42247.058510051.85247.7124
10094.77247.9613 10105.5248.434710116.23249.355910126.96249.802910140.46250.5225
#Mann= 3 , 0 , 0
9784.449    0.04       09784.449    0.04       010140.46    0.04       0
#XS Ineff= 2 , 0
       0                               0
Bank Sta=9784.449,10140.46
Exp/Cntr=0.3,0.1

Type RM Length L Ch R = 3 ,12748.37,,,
BEGIN DESCRIPTION:
END DESCRIPTION:
Bridge Culvert--1,0,-1,-1, 0
Deck Dist Width WeirC Skew NumUp NumDn MinLoCord MaxHiCord MaxSubmerge Is_Ogee
93.211950,33.000000,2.6,0, 26, 26, , , 0.95, 0, 0,0,,
 9890.54 9895.03 9905.24 9907.63 9915.46 9925.68 9935.89 9946.11 9950.15 9950.15
 9950.56 9955.0810040.1510040.1510050.4610059.0010069.4210070.4610076.2610080.08
10090.7610101.4410104.7410112.1210122.8010122.91
  247.79  247.93  248.19  248.22  248.35  248.36  248.66  248.61  248.08  248.08
  248.02  246.95  248.16  248.16  248.31  248.26  248.25  248.25  248.26  248.25
  248.10  248.03  247.99  247.87  247.85  247.85
 -752.21 -752.07 -751.81 -751.78 -751.65 -751.64 -751.34 -751.39 -751.92  243.08
  243.02  241.95  243.16 -751.84 -751.69 -751.74 -751.75 -751.75 -751.74 -751.75
 -751.90 -751.97 -752.01 -752.13 -752.15 -752.15
 9890.54 9895.03 9905.24 9907.63 9915.46 9925.68 9935.89 9946.11 9950.56 9951.63
 9951.63 9955.0810041.6310041.6310050.4610059.0010069.4210070.4610076.2610080.08
10090.7610101.4410104.7410112.1210122.8010122.91
  247.79  247.93  248.19  248.22  248.35  248.36  248.66  248.61  248.02  247.77
  247.77  246.95  248.18  248.18  248.31  248.26  248.25  248.25  248.26  248.25
  248.10  248.03  247.99  247.87  247.85  247.85
 -752.21 -752.07 -751.81 -751.78 -751.65 -751.64 -751.34 -751.39 -751.98 -752.23
  242.77  241.95  243.18 -751.82 -751.69 -751.74 -751.75 -751.75 -751.74 -751.75
 -751.90 -751.97 -752.01 -752.13 -752.15 -752.15
BR Coef=-1 , 0 , 0 ,, 0 ,,,0.8,0,1,0,
WSPro=,,,, 1 ,,,, 0 ,,,, 0 ,,,,-1 ,-1 ,-1 , 0 , 0 , 0 , 0 , 0
BC Design=,, 0 ,, 0 ,,,,,,