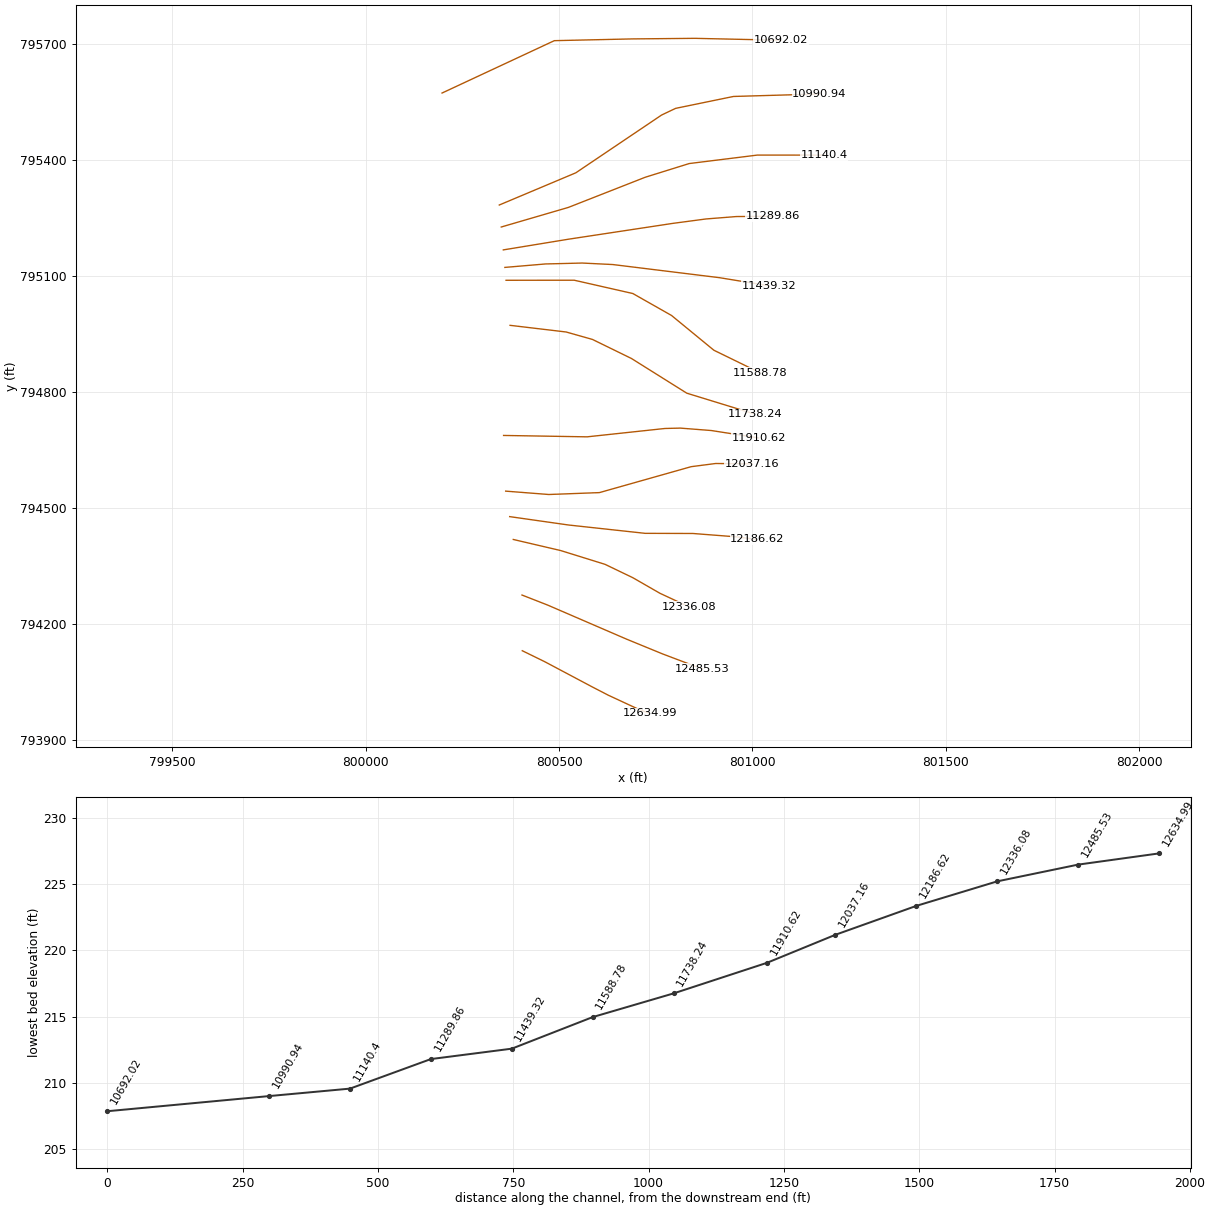
HEC-RAS study 17602_ras.prj: 17602

--- 17602_ras.g01 (geometry) --- (continued)

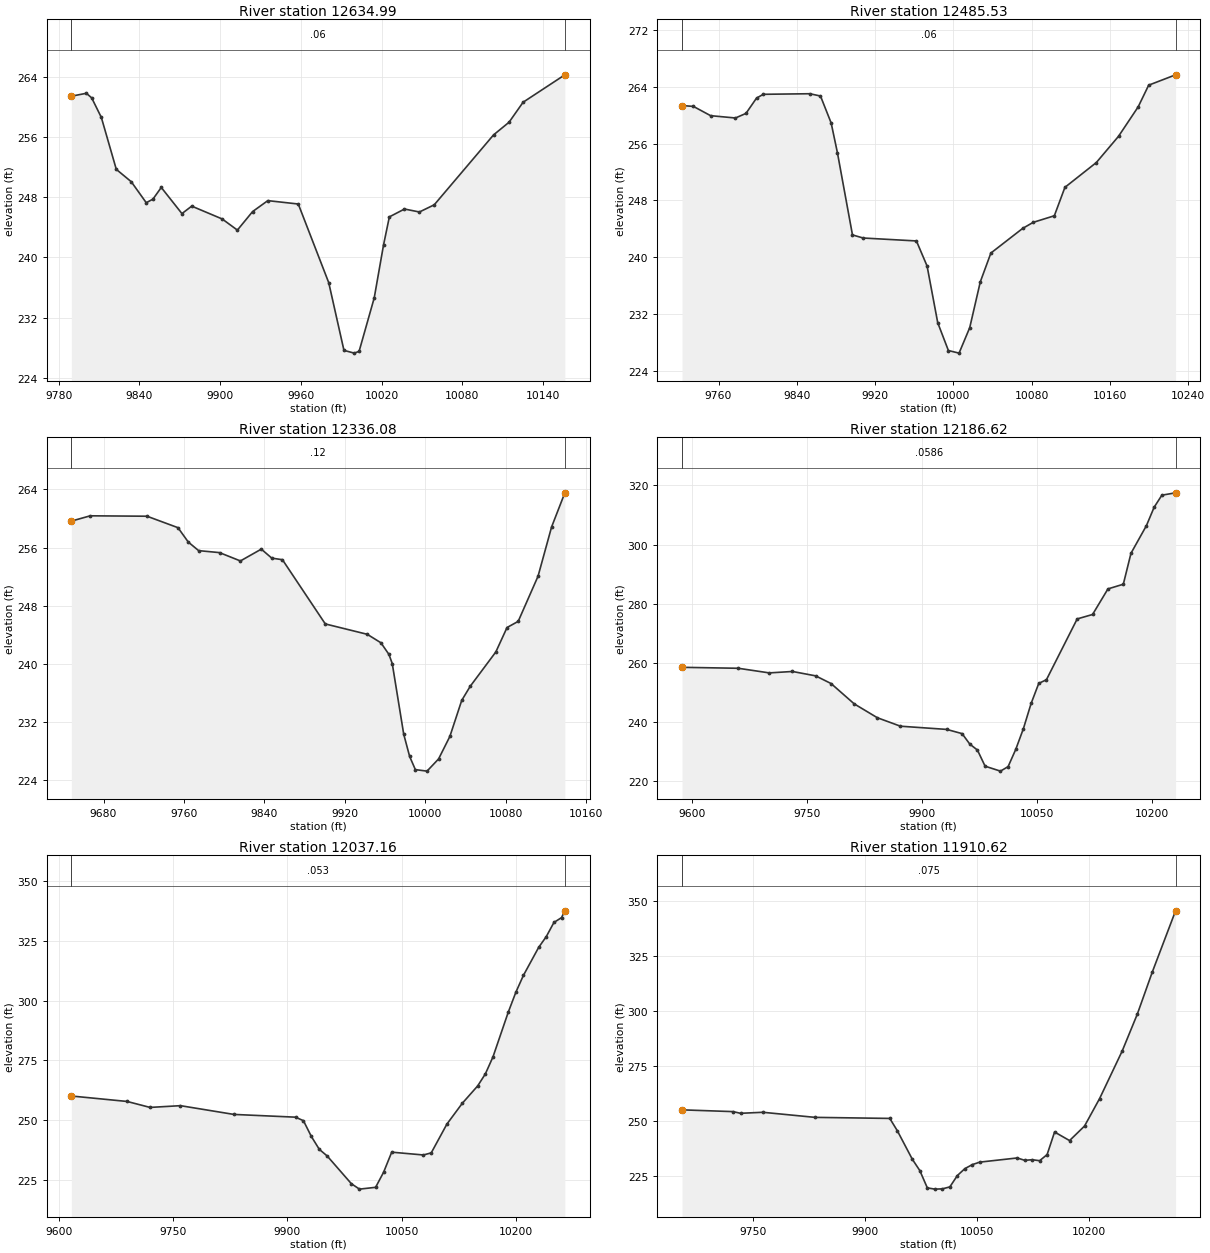
Type RM Length L Ch R = 1 ,12634.99,149.459600,149.459600,149.459600
XS GIS Cut Line= 6
 800404.95732145794131.641411201800462.763148209794103.392204453
800586.269872062794037.853416485800627.659500675794016.488418222
800702.574608786793981.701896685800733.983269928793969.653646175
#Sta/Elev= 30
9789.331261.39189800.508261.77849804.457261.17039811.639258.57629822.769 251.686
9833.899250.04559845.029247.26239850.008247.73729856.202249.28759871.574245.8185
9878.844 246.8099901.485 245.1099912.806243.62859924.127246.08759935.447247.5394
9958.089247.0904 9980.73236.65949992.051227.67679999.703227.310210003.31227.5452
10014.57234.644310021.51241.682310025.82245.384110037.07246.424510048.16 246.033
10059.19246.984210103.29256.256810114.83257.940110125.26260.590110156.31 264.227
#Mann= 3 , 0 , 0
9789.331    0.06       09789.331    0.06       010156.31    0.06       0
#XS Ineff= 2 , 0
       0                               0
Bank Sta=9789.331,10156.31
Exp/Cntr=0.3,0.1

Type RM Length L Ch R = 1 ,12485.53,149.459600,149.459600,149.459600
XS GIS Cut Line= 6
800404.189070536794275.640412589800470.961201276794249.483927098
800674.938441092794161.415305528800767.463912273794123.477690666
800850.443236001794092.012258152800871.012503835794085.230581537
#Sta/Elev= 30
9722.735261.35999734.345 261.2399751.907259.93339777.305259.60649788.045260.2529
9798.846 262.4119805.762262.94529853.305263.02529864.196262.70289875.088258.9056
9881.467 254.7319896.871243.12719907.763242.69049962.222242.27649973.113238.7442
9984.005230.74819994.897226.8307 10005.8226.465210016.69230.0533 10027.5236.5124
10038.31 240.56910070.73 244.03810081.54244.896510103.15245.824610113.96249.8301
10146.08 253.32910168.74257.023910188.85261.180810199.55264.231810227.03265.6901
#Mann= 3 , 0 , 0
9722.735    0.06       09722.735    0.06       010227.03    0.06       0
#XS Ineff= 2 , 0
       0                               0
Bank Sta=9722.735,10227.03
Exp/Cntr=0.3,0.1

Type RM Length L Ch R = 1 ,12336.08,149.459600,149.459600,149.459600
XS GIS Cut Line= 6
800381.692435289794419.283741028800504.117705635794390.655519039
800618.836160305794355.015934054800690.839273733794320.403025023
800761.085822386794280.035180223800837.296838042794244.590152439
#Sta/Elev= 30
9647.983259.63429666.796260.36449723.268 260.3089754.078258.72939764.348 256.747
9774.628255.56929795.406255.29619816.183254.14829836.961255.77559847.397254.5363
9858.006254.31889900.633 245.474 9942.36244.04719955.961242.87959963.925241.2838
9967.248240.01779978.658230.28269984.547227.2211 9990.24225.408210001.85225.2025
10013.35226.884210024.58229.986710036.36234.942910044.82 236.88810070.32241.6223
10081.43244.979310092.54245.826910112.28252.043610125.77258.829910138.95  263.53
#Mann= 3 , 0 , 0
9647.983    0.12       09647.983    0.12       010138.95    0.12       0
#XS Ineff= 2 , 0
       0                               0
Bank Sta=9647.983,10138.95
Exp/Cntr=0.3,0.1

Type RM Length L Ch R = 1 ,12186.62,149.459700,149.459700,149.459700
XS GIS Cut Line= 6
 800372.38903086794478.360359172800523.991524272 794456.75691999
800722.583152943 794435.13242019800846.227481542794434.770202447
800959.820416137794425.923435782801012.700842611794419.283263221
#Sta/Elev= 30
9586.775258.4672 9660.12258.14469700.524256.57959730.827257.06019761.042255.5786
 9781.16252.97859811.337246.11129841.515241.41619871.692238.54959932.047237.4639
9952.102236.03789962.111232.51029972.119230.47549982.123225.021710002.13 223.353
10012.13 224.87610022.13230.723210032.13237.757310042.13246.232110052.13 253.034
10062.13254.269210102.25274.837110122.31 276.33710142.37284.987710162.43286.5754
10172.46297.057510192.59 306.40210202.67312.634610212.75316.697510230.59317.4912
#Mann= 3 , 0 , 0
9586.775  0.0586       09586.775  0.0586       010230.59  0.0586       0
#XS Ineff= 2 , 0
       0                               0
Bank Sta=9586.775,10230.59
Exp/Cntr=0.3,0.1

Type RM Length L Ch R = 1 ,12037.16,126.531900,126.531900,126.531900
XS GIS Cut Line= 6
800362.010703118794544.262740358800473.496920615794535.548833505
 800604.36413448794540.457743001 800841.63347342794607.498179829
800904.935943438794615.706588456800999.318294058794614.758171029
#Sta/Elev= 30
9616.201260.13719689.464 257.8519719.531255.35839759.551256.08839829.667252.4286
9910.672251.27739921.048249.80449931.458243.19899941.868237.82629952.277235.0279
9984.051223.42519994.655221.173510015.84221.927610026.41228.291710036.99236.6372
10078.59235.460910088.92236.341110109.49248.383510129.74257.099210149.92264.3579
10159.97269.365110170.01276.498410190.02295.146810200.02303.512710210.02310.6182
10230.03322.314910240.05326.838510250.06332.735110260.08334.7685 10264.4337.6047
#Mann= 3 , 0 , 0
9616.201   0.053       09616.201   0.053       0 10264.4   0.053       0
#XS Ineff= 2 , 0
       0                               0
Bank Sta=9616.201,10264.4
Exp/Cntr=0.3,0.1

Type RM Length L Ch R = 1 ,11910.62,172.387300,172.387300,172.387300
XS GIS Cut Line= 6
800356.643774278794688.234161034800572.400827652794684.631078712
800773.711781946794706.252483728800813.536181148 794707.21070721
800893.620303113794700.967154758801015.609871626794681.924539966
#Sta/Elev= 30
9654.403255.11799722.827254.31199732.837253.54719762.849254.0098 9832.86251.6971
 9933.07251.21969943.146245.65059963.298232.65589973.374227.4979 9983.45219.6247
9993.527219.0577 10003.6219.181310013.67220.072510023.74225.238110033.81228.3807
10043.88230.219610053.95 231.34810104.09233.2366 10114.1232.155910124.11232.4292
10134.12231.990910144.13234.759410154.17245.041910174.27241.142310194.38247.7645
10214.59260.265610244.91281.909210265.12298.6185 10285.4317.929510316.47345.6449
#Mann= 3 , 0 , 0
9654.403   0.075       09654.403   0.075       010316.47   0.075       0
#XS Ineff= 2 , 0
       0                               0
Bank Sta=9654.403,10316.47
Exp/Cntr=0.3,0.1

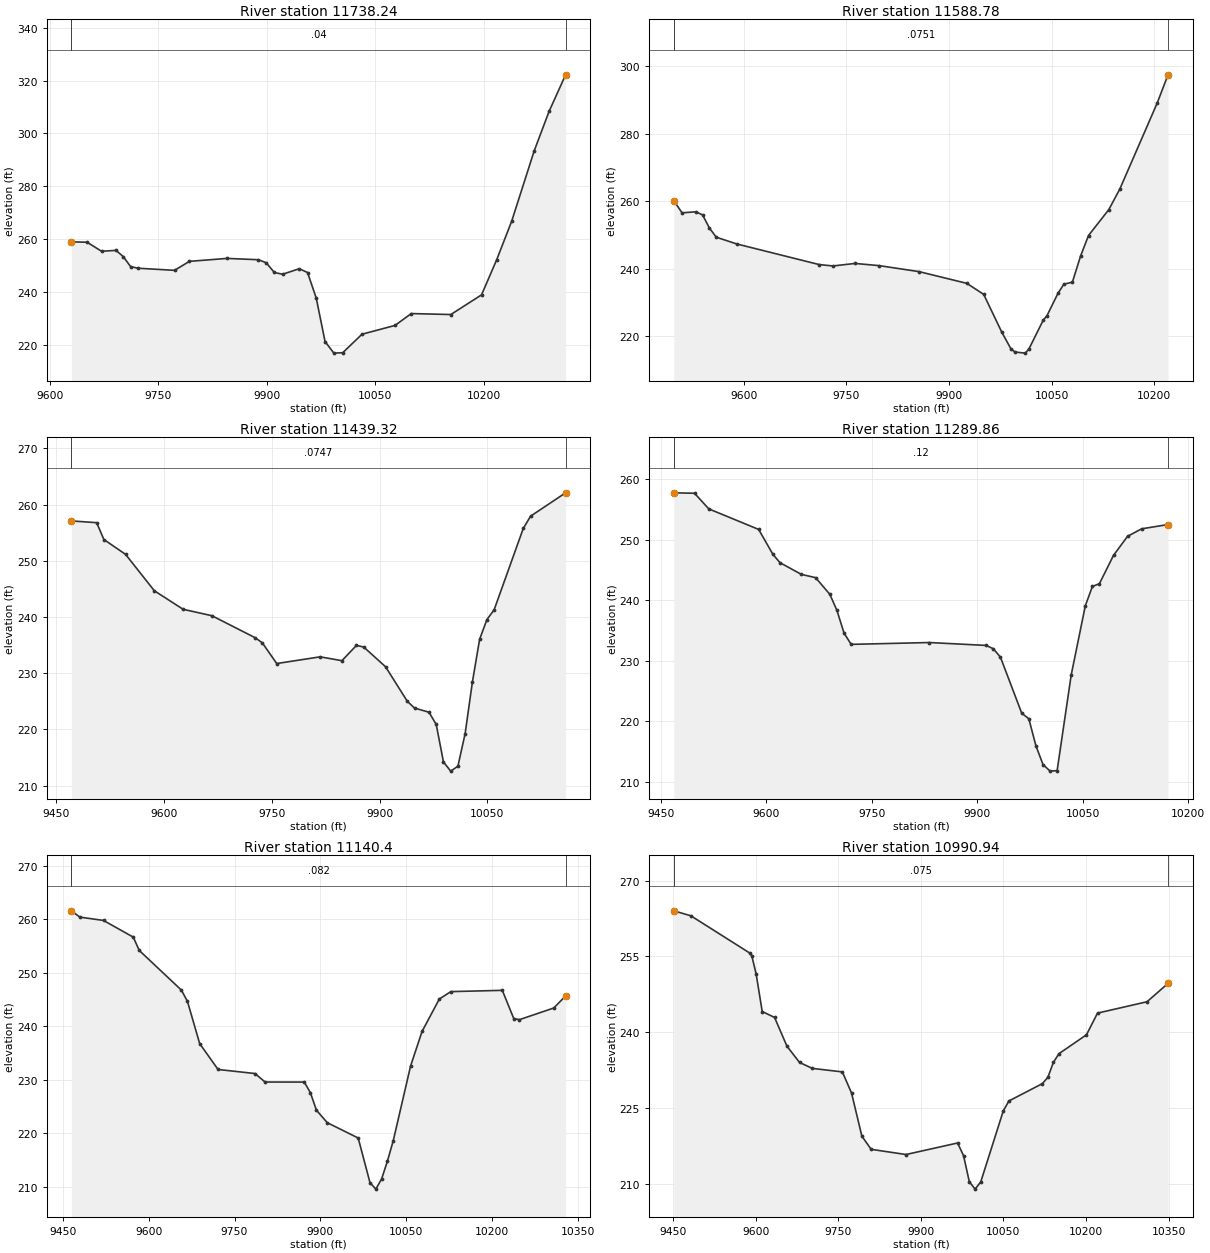
Type RM Length L Ch R = 1 ,11738.24,149.459600,149.459600,149.459600
XS GIS Cut Line= 6
800373.368012068794972.940231793800518.356638682794955.725796939
800586.430915094794936.446151999800687.126986514794887.258024516
800830.302169584794797.506722042801007.182629398794743.208981776
#Sta/Elev= 30
9629.575258.90759651.261258.77449671.311255.34919691.361255.67819701.386 253.314
9711.518249.54159721.655248.92149772.341248.11639792.913251.52329845.027252.6354
9888.361 252.1429899.207250.98829910.392247.3048 9921.88  246.649944.857248.7282
9956.346247.29899968.393237.60869980.591221.1463 9992.79216.752510005.08216.9123
10031.69223.911210077.43227.2536 10099.9231.739310154.63231.376510197.12238.8335
10217.95 252.03610238.78266.699210270.02293.418510290.66308.397610313.42322.1929
#Mann= 3 , 0 , 0
9629.575    0.04       09629.575    0.04       010313.42    0.04       0
#XS Ineff= 2 , 0
       0                               0
Bank Sta=9629.575,10313.42
Exp/Cntr=0.3,0.1

Type RM Length L Ch R = 1 ,11588.78,149.459600,149.459600,149.459600
XS GIS Cut Line= 6
800362.938298517795089.405366531800539.229504614795089.580042579
800690.742906403795055.204268954800790.749389016794998.502228736
800900.360712382794908.538699781801019.827313105 794850.27848388
#Sta/Elev= 30
9497.477260.14829509.551256.53469529.573256.83959539.584255.91729549.594252.0184
9559.605249.31089589.626247.30989710.037241.20529730.253 240.7929762.614241.5417
9798.279240.87629856.233239.10849926.057235.6357 9950.69232.36569977.089221.1827
9990.289216.31139996.405 215.28910011.55214.965910016.86216.225410037.69224.7239
10043.06225.995110059.24232.667710067.91235.398510080.33235.982810092.36243.7422
10103.93249.817110133.71257.521510149.66263.567310204.41289.072610220.18297.4241
#Mann= 3 , 0 , 0
9497.477  0.0751       09497.477  0.0751       010220.18  0.0751       0
#XS Ineff= 2 , 0
       0                               0
Bank Sta=9497.477,10220.18
Exp/Cntr=0.3,0.1

Type RM Length L Ch R = 1 ,11439.32,149.459600,149.459600,149.459600
XS GIS Cut Line= 6
800359.955593206795122.712242535 800464.86293251795131.628119111
800560.050790447795133.981093092 800639.21130786795130.088280157
800914.512583181795096.180303723801042.913747437795075.210359157
#Sta/Elev= 30
9471.398257.11089506.568256.79729516.604253.80149546.713251.16339586.823244.6756
9626.836241.38039666.848240.23939726.916236.33139736.928235.41689756.981231.7299
9817.369232.92179847.679232.23869867.886 234.9639877.989234.66419908.299 231.163
9938.587225.01289948.643223.80189968.755223.06629978.811220.88989988.867214.2188
9998.923212.583810008.97213.464210019.02 219.26810029.08 228.41110039.17236.0482
10049.27239.546110059.36241.298310099.86 255.76710110.02257.955110158.72262.1094
#Mann= 3 , 0 , 0
9471.398  0.0747       09471.398  0.0747       010158.72  0.0747       0
#XS Ineff= 2 , 0
       0                               0
Bank Sta=9471.398,10158.72
Exp/Cntr=0.3,0.1

Type RM Length L Ch R = 1 ,11289.86,149.459700,149.459700,149.459700
XS GIS Cut Line= 6
800355.901772231795167.979910125800524.679571589795195.671997227
800794.478527769795236.586308959800880.352039084795248.015201246
800958.956275681795254.209633175 801052.49506368795254.860038475
#Sta/Elev= 30
9468.215257.76649497.703257.6976 9517.97255.11519588.906251.72299609.173247.6117
9619.307246.22099649.688244.29859669.917243.75639690.146241.0089 9700.26238.3453
9710.374234.60399720.489232.73629831.746233.0399 9912.66232.56129922.748232.0078
9932.836230.6225  9963.1221.36989973.189220.45399983.277215.99379993.365 212.891
10003.43211.799610013.46211.880710033.52 227.70410053.58239.118110063.61242.2984
10073.64242.765110093.66 247.43910113.67250.584810133.67251.823310171.17252.5267
#Mann= 3 , 0 , 0
9468.215    0.12       09468.215    0.12       010171.17    0.12       0
#XS Ineff= 2 , 0
       0                               0
Bank Sta=9468.215,10171.17
Exp/Cntr=0.3,0.1

Type RM Length L Ch R = 1 , 11140.4,149.459600,149.459600,149.459600
XS GIS Cut Line= 6
800350.601874203795227.162104811800524.183118791795277.831937897
800722.917867691795355.827800391800836.531222784795391.226492255
801012.808333504795413.127869297801185.600293347795413.041190774
#Sta/Elev= 30
9464.722261.5368 9479.58260.36269520.933259.74059572.959256.62299583.375254.1418
9657.113246.73099667.752244.6093 9689.03236.7542  9721.2231.91159785.892231.1547
 9803.42229.56919871.954229.55999882.574227.59749893.195224.30949912.152221.9811
9966.244219.11229986.856210.78569997.071 209.57110007.23211.485910017.37214.8031
 10027.5218.598310057.82232.551610077.95239.030610108.12245.067510128.17246.4511
10218.25246.689710238.25241.417510248.25241.216510308.26243.396110328.88  245.64
#Mann= 3 , 0 , 0
9464.722   0.082       09464.722   0.082       010328.88   0.082       0
#XS Ineff= 2 , 0
       0                               0
Bank Sta=9464.722,10328.88
Exp/Cntr=0.3,0.1

Type RM Length L Ch R = 1 ,10990.94,298.919200,298.919200,298.919200
XS GIS Cut Line= 6
800345.507490645 795284.04938792800543.364374558795367.279692782
800765.250990061795516.736038915800801.439699271795533.908176403
800950.880318713795564.683622142801173.081571986795571.090048015
#Sta/Elev= 30
 9451.08264.0078 9482.09263.02949589.872 255.6129592.994255.04749600.813251.4634
9611.754244.1029 9634.19242.94049656.653237.26989679.571234.04239702.816232.8686
9757.358232.17589774.048228.00469792.862219.46829809.712216.87219872.989215.8472
9966.717218.12639977.578215.63229988.065 210.4739998.551209.008610008.88210.4512
10049.78224.463610059.98226.432610120.74229.855210130.81 231.10310140.84 234.054
10150.87 235.77110200.99239.5137   10221243.790710311.02246.0411 10349.1249.6664
#Mann= 3 , 0 , 0
 9451.08   0.075       0 9451.08   0.075       0 10349.1   0.075       0
#XS Ineff= 2 , 0
       09900.858                       0
Bank Sta=9451.08,10349.1
Exp/Cntr=0.3,0.1

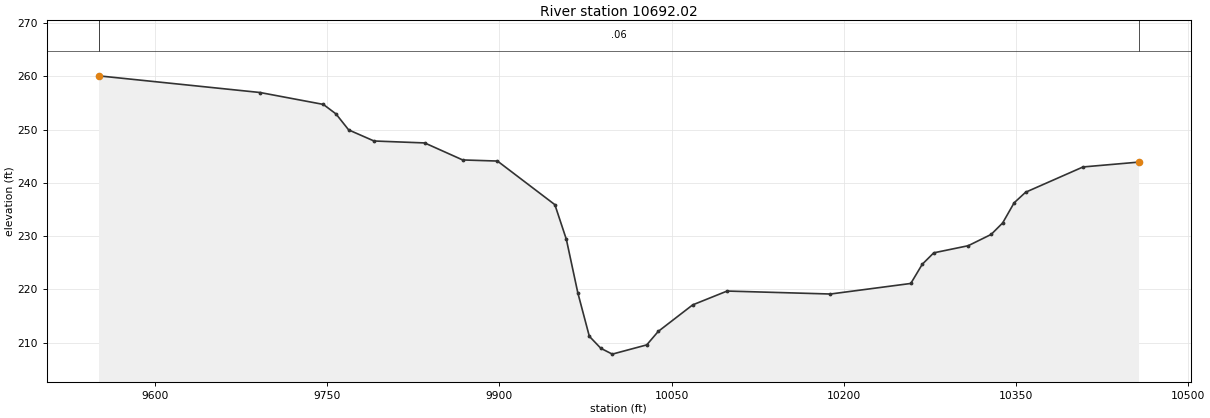
Type RM Length L Ch R = 1 ,10692.02,297.286600,297.286600,297.286600
XS GIS Cut Line= 5
800197.523827761795573.541725516800487.888411045795708.958392173
800690.108176292795713.491374273800851.776686011795714.967576635
801073.346901164795710.038454751
#Sta/Elev= 30
9550.767 260.0979691.425256.96739746.595254.73179757.629252.94349768.663249.9469
9790.731247.86769834.867247.50229867.969244.31069898.275244.10239948.287235.9143
 9958.29229.40089968.292219.35199978.295211.21589988.297208.9615  9998.3207.8657
10028.31   209.610038.31212.125210068.32217.107410098.32219.704910188.32219.1468
10258.33221.128810268.33224.736810278.34 226.87610308.34228.211810328.35230.3325
10338.35232.487910348.35236.268210358.36238.251910408.37242.994410456.73243.9011
#Mann= 3 , 0 , 0
9550.767    0.06       09550.767    0.06       010456.73    0.06       0
#XS Ineff= 2 , 0
       0                               0
Bank Sta=9550.767,10456.73
Exp/Cntr=0.3,0.1