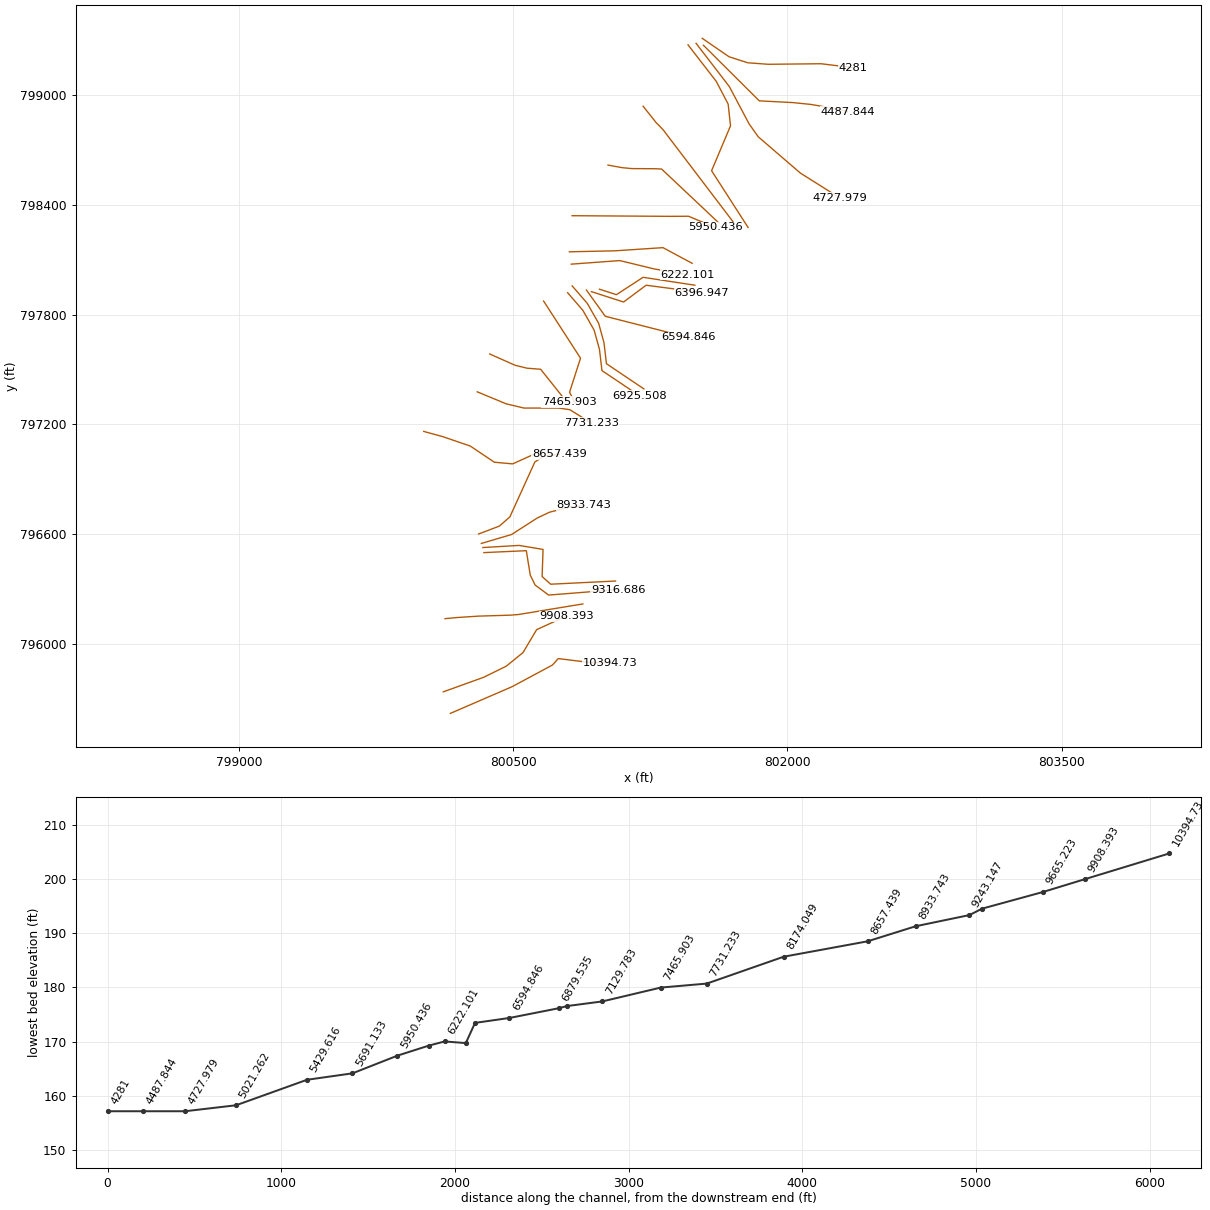
HEC-RAS study 17602_ras.prj: 17602

--- 17602_ras.g01 (geometry) --- (continued)

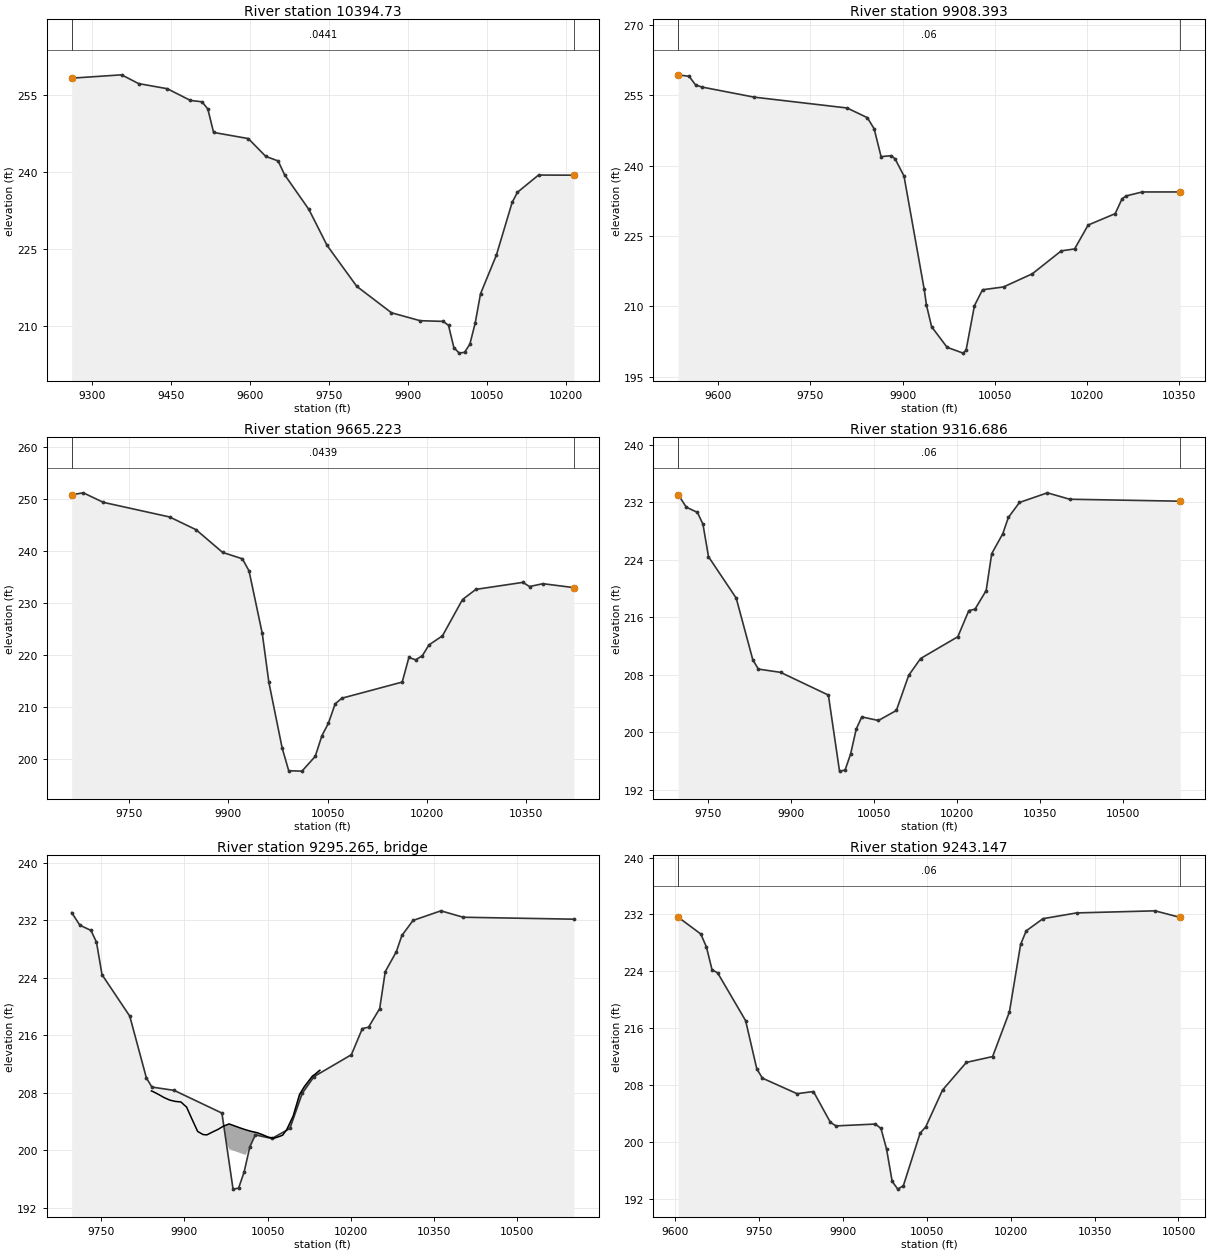
Type RM Length L Ch R = 1 ,10394.73,486.339800,486.339800,486.339800
XS GIS Cut Line= 6
800156.815695166795619.540567965800494.019058269795765.379940617
800715.367188227795884.111126591800746.545434204795919.280351338
800925.408625537795897.144337789801032.075864938795897.568250931
#Sta/Elev= 30
9260.394258.32919355.257 258.9819387.662 257.2729442.129 256.2749486.094253.9895
9508.076253.72469519.067252.33169530.058247.75779596.005246.56019629.058243.0999
9652.658242.19679664.858239.53219711.164232.74259745.642225.7438 9802.04217.7714
 9868.04212.61689922.497211.0716 9966.16 210.942 9976.35210.1726 9986.54205.8363
9996.721 204.75510006.84204.919810016.95 206.50210027.06210.623510037.16216.3176
10067.25223.831110097.34234.146310107.37 236.10410147.37239.453410214.46239.4251
#Mann= 3 , 0 , 0
9260.394  0.0441       09260.394  0.0441       010214.46  0.0441       0
#XS Ineff= 2 , 0
       0                               0
Bank Sta=9260.394,10214.46
Exp/Cntr=0.3,0.1

Type RM Length L Ch R = 1 ,9908.393,243.169800,243.169800,243.169800
XS GIS Cut Line= 6
800118.018053487795737.294813711800339.756230467795817.316210272
800462.332993337795877.694530961800553.803743673795951.820315164
800628.513411045796077.447975516800791.273827732796151.666725501
#Sta/Elev= 30
9535.384 259.3799553.299259.05979563.848257.19929574.398 256.7669658.797254.6194
 9809.94252.30629842.931250.23369853.928247.86439865.189241.92969881.833 242.129
9888.082241.41649902.384237.80099935.238213.63799938.933210.24649947.289205.6381
9972.424201.24829998.427200.001710003.29200.619410016.89210.133610030.01213.5209
10064.11214.121210111.01216.937410157.92221.818210179.65222.231810201.63227.3288
10245.59229.758610256.58232.884210263.03233.534710289.55234.3864 10351.4234.3926
#Mann= 3 , 0 , 0
9535.384    0.06       09535.384    0.06       0 10351.4    0.06       0
#XS Ineff= 2 , 0
       0                               0
Bank Sta=9535.384,10351.4
Exp/Cntr=0.3,0.1

Type RM Length L Ch R = 1 ,9665.223,348.536700,348.536700,348.536700
XS GIS Cut Line= 6
800127.428378149796137.634671949800192.275635928796143.719098255
800311.225090116796151.478139669800482.082131743796156.624763876
800530.002981037796160.339216471800881.117577732796218.072975516
#Sta/Elev= 30
9662.918250.81989680.567251.18559710.698249.3573 9810.95246.54029851.029244.0837
9891.046239.72279921.059238.48479931.063236.15849951.072224.12359961.076214.7004
9981.085202.10369991.089197.6833 10011.1 197.61610031.14200.455810041.17204.4086
 10051.2206.874110061.23210.555910071.34211.650510162.63214.757510172.76219.5051
10182.89219.041610193.02219.821510203.15221.919910223.41223.646810253.81 230.651
10274.07232.602910344.98233.947310355.11233.150110375.37233.693610422.09232.9389
#Mann= 3 , 0 , 0
9662.918  0.0439       09662.918  0.0439       010422.09  0.0439       0
#XS Ineff= 2 , 0
       0                               0
Bank Sta=9662.918,10422.09
Exp/Cntr=0.3,0.1

Type RM Length L Ch R = 1 ,9316.686,73.539400,73.539400,73.539400
XS GIS Cut Line= 6
800340.209989816796498.893766969 800572.09615922796509.328644618
800593.662568122796375.824574053800620.212539345796321.500847399
800693.996904165796266.619764701801073.595738351796296.611524209
#Sta/Elev= 30
9696.403233.06069711.208231.30369731.228230.57579741.238228.93469751.248224.4097
9801.299218.64469831.329210.0411 9841.34208.7668 9881.38208.30919967.706205.1457
9987.803194.56029997.852194.7029 10007.9196.967710017.95200.4103   10028202.1091
10058.05201.608510090.42203.004110112.68207.890110134.17210.235610201.42213.2697
10221.24216.910410232.39 217.10110252.56219.696310262.57224.834410282.59227.6106
10292.59229.867510312.71231.959810363.04233.3012 10403.3232.409510603.07232.1373
#Mann= 3 , 0 , 0
9696.403    0.06       09696.403    0.06       010603.07    0.06       0
#XS Ineff= 2 , 0
       09960.496        10053.15       0
Bank Sta=9696.403,10603.07
Exp/Cntr=0.3,0.1

Type RM Length L Ch R = 3 ,9295.265,,,
BEGIN DESCRIPTION:
END DESCRIPTION:
Bridge Culvert--1,0,-1,-1, 0
Deck Dist Width WeirC Skew NumUp NumDn MinLoCord MaxHiCord MaxSubmerge Is_Ogee
18.269700,37.000000,2.6,0, 43, 43, , , 0.95, 0, 0,0,,
 9840.43 9843.53 9853.57 9863.62 9873.67 9883.71 9893.76 9900.87 9903.80 9913.85
 9923.89 9933.56 9940.46 9950.49 9960.51 9970.54 9975.15 9975.15 9980.56 9986.29
 9990.5910000.6210010.6510020.6810027.1510027.1510030.7110040.7510050.7810058.39
10061.2010072.8610077.3810084.5110096.1610096.8510107.8210116.3210119.4710131.13
10135.7910142.7810144.58
  208.23  208.13  207.73  207.29  206.95  206.77  206.69  206.18  206.00  204.27
  202.59  202.16  202.11  202.50  202.87  203.33  203.47  203.47  203.64  203.48
  203.36  203.08  202.82  202.60  202.49  202.49  202.43  202.15  201.82  201.68
  201.63  201.93  202.07  202.82  204.71  204.87  207.74  208.81  209.13  210.30
  210.55  211.01  211.10
 -791.77 -791.87 -792.27 -792.71 -793.05 -793.23 -793.31 -793.82 -794.00 -795.73
 -797.41 -797.84 -797.89 -797.50 -797.13 -796.67 -796.53  199.97  200.14  199.98
  199.86  199.58  199.32  199.10  198.99 -797.51 -797.57 -797.85 -798.18 -798.32
 -798.37 -798.07 -797.93 -797.18 -795.29 -795.13 -792.26 -791.19 -790.87 -789.70
 -789.45 -788.99 -788.90
 9840.43 9843.53 9853.57 9863.62 9873.67 9883.71 9893.76 9900.87 9903.80 9913.85
 9923.89 9933.56 9940.46 9950.49 9960.51 9970.54 9980.56 9984.28 9984.28 9986.29
 9990.5910000.6210010.6510020.6810030.7110036.2810036.2810040.7510050.7810058.39
10061.2010072.8610077.3810084.5110096.1610096.8510107.8210116.3210119.4710131.13
10135.7910142.7810144.58
  208.23  208.13  207.73  207.29  206.95  206.77  206.69  206.18  206.00  204.27
  202.59  202.16  202.11  202.50  202.87  203.33  203.64  203.54  203.54  203.48
  203.36  203.08  202.82  202.60  202.43  202.28  202.28  202.15  201.82  201.68
  201.63  201.93  202.07  202.82  204.71  204.87  207.74  208.81  209.13  210.30
  210.55  211.01  211.10
 -791.77 -791.87 -792.27 -792.71 -793.05 -793.23 -793.31 -793.82 -794.00 -795.73
 -797.41 -797.84 -797.89 -797.50 -797.13 -796.67 -796.36 -796.46  200.04  199.98
  199.86  199.58  199.32  199.10  198.93  198.78 -797.72 -797.85 -798.18 -798.32
 -798.37 -798.07 -797.93 -797.18 -795.29 -795.13 -792.26 -791.19 -790.87 -789.70
 -789.45 -788.99 -788.90
BR Coef=-1 , 0 , 0 ,, 0 ,,,0.8,0,1,0,
WSPro=,,,, 1 ,,,, 0 ,,,, 0 ,,,,-1 ,-1 ,-1 , 0 , 0 , 0 , 0 , 0
BC Design=,, 0 ,, 0 ,,,,,,

Type RM Length L Ch R = 1 ,9243.147,309.404200,309.404200,309.404200
XS GIS Cut Line= 6
800334.450486124796526.609057501800532.713160992796538.203365952
800663.669661045 796516.25005886800658.511407852796367.767031446
800705.468357146 796326.02752094801060.254196346796343.418983668
#Sta/Elev= 30
9605.145  231.629645.764229.24129655.781227.41929665.798224.22079675.815223.7809
  9725.9217.05489745.934210.25829755.951208.97259817.799206.78959847.176207.0956
9877.472202.76179887.561202.26029957.931 202.5219967.937201.90229977.943198.9992
9987.949194.46969997.955193.369510007.96193.847610037.98201.248510047.99202.1237
   10078207.297510120.68211.192510167.62212.010910197.66218.293610217.68227.7858
10227.69229.691510257.73231.4008 10317.8232.209810457.97232.504210503.28231.5752
#Mann= 3 , 0 , 0
9605.145    0.06       09605.145    0.06       010503.28    0.06       0
#XS Ineff= 2 , 0
       09969.155        10061.46       0
Bank Sta=9605.145,10503.28
Exp/Cntr=0.3,0.1

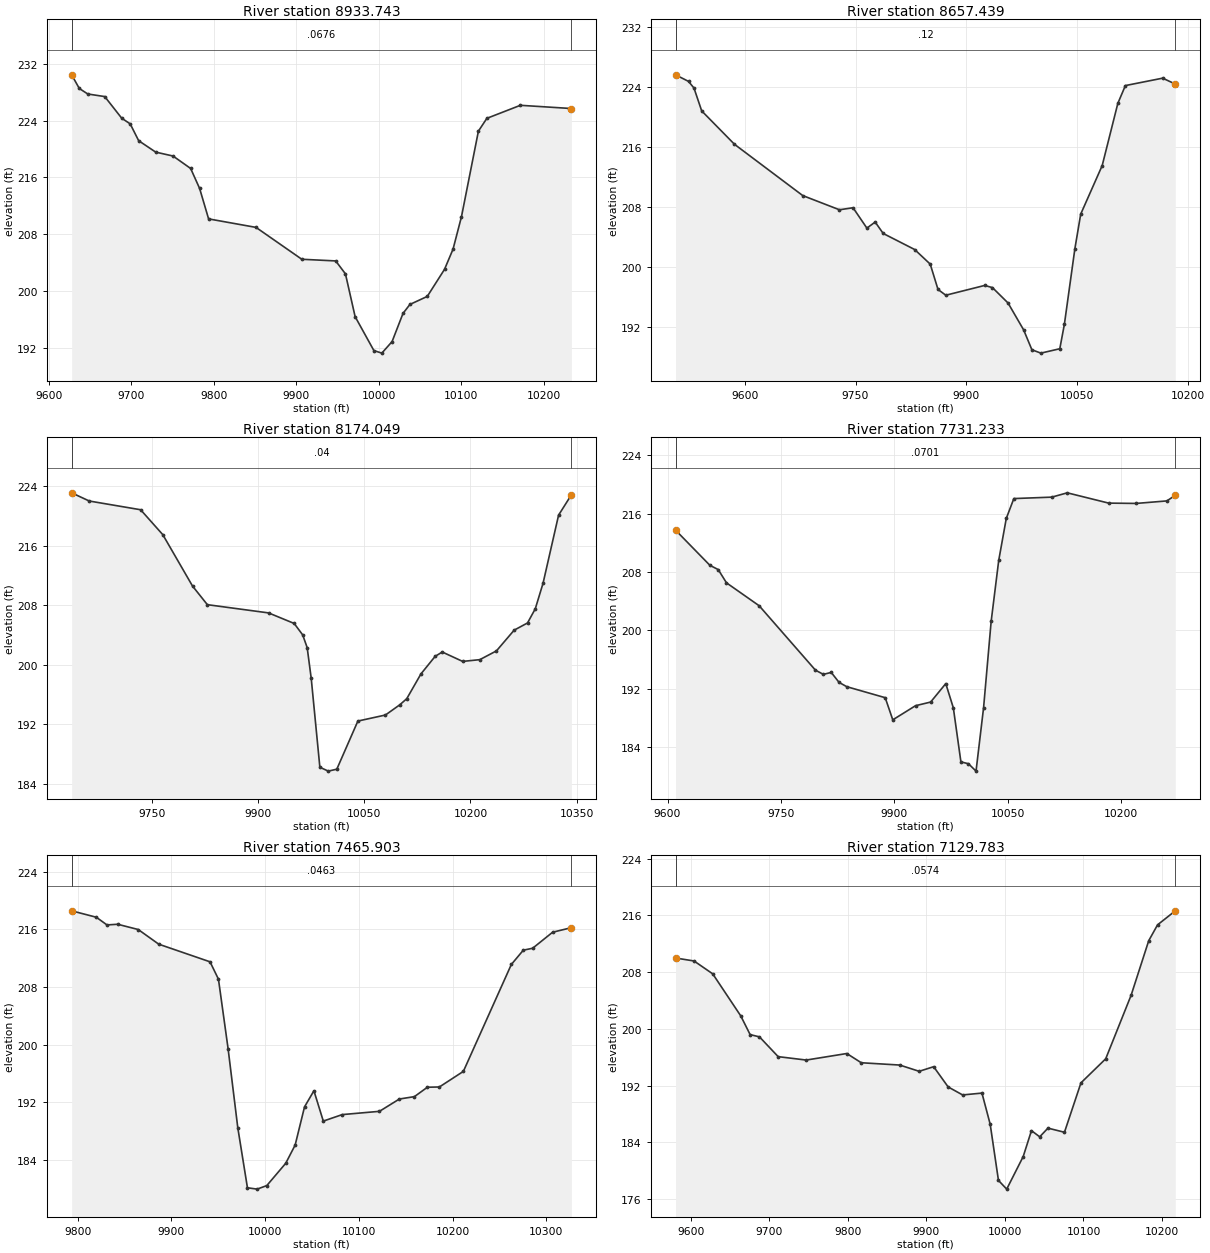
Type RM Length L Ch R = 1 ,8933.743,276.303900,276.303900,276.303900
XS GIS Cut Line= 6
800325.951845217796548.898160634 800491.28444127796597.807127149
800631.947690696796688.137061323800698.815147843796719.732101229
800796.351170122796744.762833838800886.333407869796757.061868717
#Sta/Elev= 30
9627.893230.43079637.165228.51299647.444227.73669668.003227.37319688.561224.3345
 9698.84223.53639709.119221.1715 9729.77219.56469750.818219.01399772.139217.2643
9783.017214.45619793.895210.17859851.372 208.9829906.903204.50059947.969204.2676
9959.792202.44769971.505 196.4389994.259191.664710003.89191.305510016.33192.9321
10029.57 196.89210037.94198.149910058.97199.278510079.86203.079710090.22205.9278
10100.46210.499810120.95222.5103 10131.2224.314410171.85226.146210233.68225.6932
#Mann= 3 , 0 , 0
9627.893  0.0676       09627.893  0.0676       010233.68  0.0676       0
#XS Ineff= 2 , 0
       0                               0
Bank Sta=9627.893,10233.68
Exp/Cntr=0.3,0.1

Type RM Length L Ch R = 1 ,8657.439,483.390200,483.390200,483.390200
XS GIS Cut Line= 6
 800310.87695778796600.607507942800424.922764632796643.908602215
800482.165758088796694.328120098800618.765643725796994.550188072
800668.564290373 797026.33664193800752.074603695797035.930850775
#Sta/Elev= 30
9506.585225.6477 9524.13224.77269531.502223.88399541.931220.83739586.274216.3829
9678.591209.54229728.229207.64759746.641207.91739765.383205.20069776.577 206.012
9787.427204.48699829.993202.34439851.038200.3955 9861.56197.01919872.082196.2498
9924.694197.55439935.216197.2635 9956.26195.21529977.451191.61079988.527188.9756
10000.67188.525510026.28189.110210032.46192.3563 10046.7202.468710054.57207.0691
10083.61213.540710104.77221.8397   10115224.2151 10165.4225.2031 10182.5224.4166
#Mann= 3 , 0 , 0
9506.585    0.12       09506.585    0.12       0 10182.5    0.12       0
#XS Ineff= 2 , 0
       0                               0
Bank Sta=9506.585,10182.5
Exp/Cntr=0.3,0.1

Type RM Length L Ch R = 1 ,8174.049,442.816200,442.816200,442.816200
XS GIS Cut Line= 6
 800010.99163121 797161.73933126800114.652705759797133.263484865
800265.906438589 797081.58558321800397.176605523796993.246586621
800497.437022209796984.132003292800661.499522179797058.350753278
#Sta/Elev= 30
 9636.28223.14069661.177222.0375 9733.77220.86299765.129217.50649807.096210.5965
9828.079208.08659914.627206.97789950.788205.55939962.841204.01779969.196202.2988
9974.895 198.1699987.107186.20739999.002185.681810011.06185.942910040.84192.4208
10079.79193.234210099.87194.594410109.91195.4281   10130198.768910150.08 201.133
10160.12201.713710188.93200.4498 10213.2 200.68610236.72201.867410261.72204.6553
10280.62205.6247 10291.6207.534710302.58210.974510324.53220.139110342.64222.8761
#Mann= 3 , 0 , 0
 9636.28    0.04       0 9636.28    0.04       010342.64    0.04       0
#XS Ineff= 2 , 0
       0                               0
Bank Sta=9636.28,10342.64
Exp/Cntr=0.3,0.1

Type RM Length L Ch R = 1 ,7731.233,265.329300,265.329300,265.329300
XS GIS Cut Line= 6
800303.639619811797378.221651539800461.954553967797312.627742426
800558.779356284 797289.55537034800749.867444295797289.429722315
800810.097688396797280.519286608800926.360380189797208.227631823
#Sta/Elev= 30
9610.606213.72689656.038208.90779667.022208.3255 9677.98206.50889721.241203.3665
9795.673194.54659806.107193.97619816.542194.23799826.858192.87699837.055192.2857
 9887.93190.77879897.948187.74449928.003189.67989948.028190.18039968.041 192.709
9978.048189.38469988.054181.98819998.061181.731410008.07180.720310018.07189.4272
10028.07201.229110038.08209.583210048.08215.331710058.08218.050510108.26218.2471
10128.74218.837210183.51217.428910219.75217.383910260.44 217.72910271.65218.4902
#Mann= 3 , 0 , 0
9610.606  0.0701       09610.606  0.0701       010271.65  0.0701       0
#XS Ineff= 2 , 0
       0                               0
Bank Sta=9610.606,10271.65
Exp/Cntr=0.3,0.1

Type RM Length L Ch R = 1 ,7465.903,336.120000,336.120000,336.120000
XS GIS Cut Line= 6
800371.938059598797585.141806796800510.572258919 797523.55133003
800575.736617267797507.551738426800650.451818138797501.704226375
800767.961554974 797354.36436528800806.898827732797322.239642188
#Sta/Elev= 30
9793.574218.54989819.862217.66259831.262216.59459842.658216.68819864.581215.9603
9886.504213.92659941.194211.48379950.186209.07899960.496199.41839970.806188.4987
9981.116180.16829991.426179.981110001.76180.4712   10022183.569810032.01186.0912
10042.02191.382710052.03193.611210062.04189.410110082.26190.310710121.94190.7623
10143.19 192.46910159.23192.7988 10173.1194.103210185.89194.138510211.47196.2994
10262.64211.114210275.43213.098510285.37213.361810306.67215.583410326.72216.2158
#Mann= 3 , 0 , 0
9793.574  0.0463       09793.574  0.0463       010326.72  0.0463       0
#XS Ineff= 2 , 0
       0                               0
Bank Sta=9793.574,10326.72
Exp/Cntr=0.3,0.1

Type RM Length L Ch R = 1 ,7129.783,204.275300,204.275300,204.275300
XS GIS Cut Line= 4
800666.707855523797874.757003278800868.530772209797562.257003278
800808.634938836797376.059086636800839.884938836797314.861169949
#Sta/Elev= 30
9580.587209.99659604.107209.57799627.915207.76499663.628201.83639675.532199.2037
9687.436198.88329711.244196.09619746.957195.61519798.627196.5377 9817.06195.2362
9865.999 194.9129890.789194.02939909.221194.67939927.653191.82889946.086190.6996
9970.722190.95989981.226186.55819991.731178.653710002.24177.426210023.24182.0184
10033.75185.668410044.25184.798710054.76186.021910075.77185.440610096.78192.4041
10128.29195.793610160.61204.739310183.06212.435910194.29 214.669 10216.9216.6461
#Mann= 3 , 0 , 0
9580.587  0.0574       09580.587  0.0574       0 10216.9  0.0574       0
#XS Ineff= 2 , 0
       09961.963                       0
Bank Sta=9580.587,10216.9
Exp/Cntr=0.3,0.1

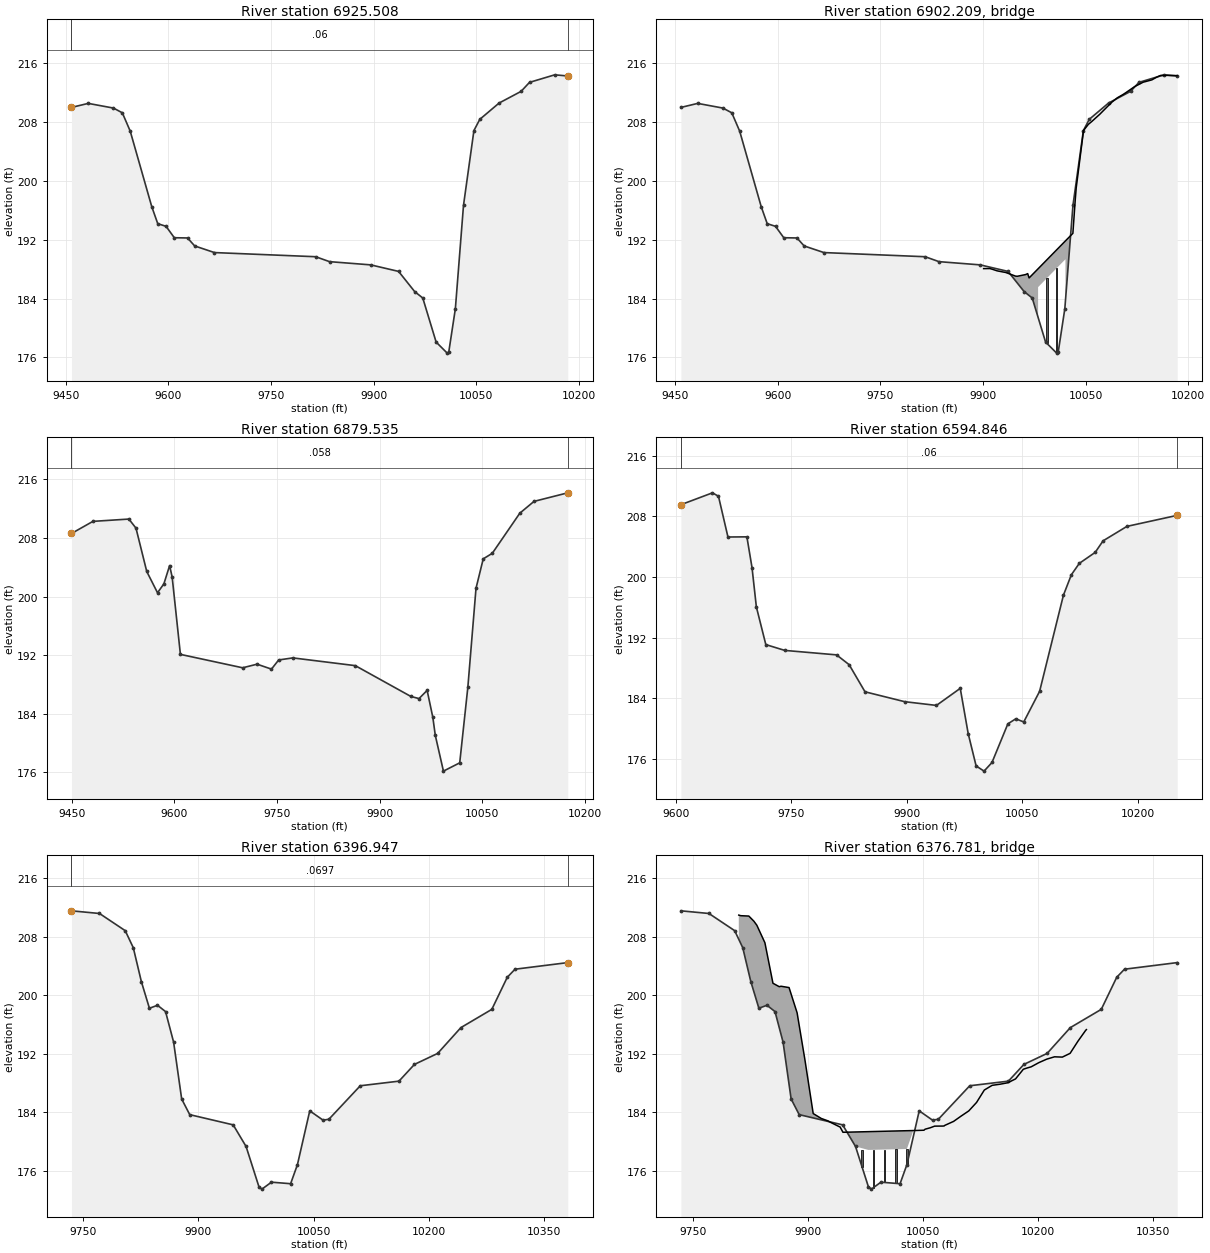
Type RM Length L Ch R = 1 ,6925.508,45.973300,45.973300,45.973300
XS GIS Cut Line= 6
800798.122995341797920.351947371800881.248322185797824.192484113
800942.997887271797715.619278662 800972.27490043797609.815725599
 800985.71675458 797494.53349416801190.529303187797356.858668983
#Sta/Elev= 30
9458.337210.01059482.862210.55739519.712209.92079532.664209.27839544.212206.7832
9575.684196.5053 9584.47194.18679596.604193.82499608.666192.27459627.992192.2427
9638.466191.15679667.371190.25389815.354189.68899835.603189.01869895.898188.5794
9936.587187.6898 9960.03184.94839971.938184.06789991.453 178.07210007.66176.5681
10009.87176.678610019.57182.602910031.48196.6887 10046.7206.8586 10055.3208.3867
10083.53210.605810115.67212.194510127.96213.418410164.83 214.44610183.91214.2897
#Mann= 3 , 0 , 0
9458.337    0.06       09458.337    0.06       010183.91    0.06       0
#XS Ineff= 2 , 0
       09964.432        10054.48       0
Bank Sta=9458.337,10183.91
Exp/Cntr=0.3,0.1

Type RM Length L Ch R = 3 ,6902.209,,,
BEGIN DESCRIPTION:
END DESCRIPTION:
Bridge Culvert--1,0,-1,-1, 0
Deck Dist Width WeirC Skew NumUp NumDn MinLoCord MaxHiCord MaxSubmerge Is_Ogee
15.486650,15.000000,2.6,0, 40, 40, , , 0.95, 0, 0,0,,
 9900.89 9910.00 9914.02 9920.48 9930.96 9932.60 9937.98 9947.56 9950.09 9962.20
 9965.30 9967.33 9980.51 9980.5110020.5110020.5110031.3510034.8410036.2510046.95
10053.9910059.0610071.1610071.7310072.4910083.7310088.1710096.3610104.5510108.99
10120.9310121.6110134.2410137.3110146.8610153.6910159.4910170.0710172.1210183.64
  188.07  188.08  187.97  187.77  187.58  187.56  187.38  187.05  187.03  187.26
  187.39  186.80  188.05  188.05  191.85  191.85  192.87  197.46  199.08  206.87
  207.71  208.10  209.12  209.18  209.25  210.30  210.71  211.32  211.76  212.03
  212.80  212.84  213.45  213.52  213.76  214.12  214.36  214.37  214.36  214.34
 -811.93 -811.92 -812.03 -812.23 -812.42 -812.44 -812.62 -812.95 -812.97 -812.74
 -812.61 -813.20 -811.95  185.55  189.35 -808.15 -807.13 -802.54 -800.92 -793.13
 -792.29 -791.90 -790.88 -790.82 -790.75 -789.70 -789.29 -788.68 -788.24 -787.97
 -787.20 -787.16 -786.55 -786.48 -786.24 -785.88 -785.64 -785.63 -785.64 -785.66
 9900.89 9910.00 9914.02 9920.48 9930.96 9932.60 9937.98 9947.56 9950.09 9962.20
 9965.30 9967.33 9981.77 9981.7710021.7710021.7710031.3510034.8410036.2510046.95
10053.9910059.0610071.1610071.7310072.4910083.7310088.1710096.3610104.5510108.99
10120.9310121.6110134.2410137.3110146.8610153.6910159.4910170.0710172.1210183.64
  188.07  188.08  187.97  187.77  187.58  187.56  187.38  187.05  187.03  187.26
  187.39  186.80  188.17  188.17  191.97  191.97  192.87  197.46  199.08  206.87
  207.71  208.10  209.12  209.18  209.25  210.30  210.71  211.32  211.76  212.03
  212.80  212.84  213.45  213.52  213.76  214.12  214.36  214.37  214.36  214.34
 -811.93 -811.92 -812.03 -812.23 -812.42 -812.44 -812.62 -812.95 -812.97 -812.74
 -812.61 -813.20 -811.83  185.67  189.47 -808.03 -807.13 -802.54 -800.92 -793.13
 -792.29 -791.90 -790.88 -790.82 -790.75 -789.70 -789.29 -788.68 -788.24 -787.97
 -787.20 -787.16 -786.55 -786.48 -786.24 -785.88 -785.64 -785.63 -785.64 -785.66
Pier Skew, UpSta & Num, DnSta & Num=  ,9993.51, 2 ,9994.77, 2 , 0 , 0 , 0 ,,
    2.00    2.00
 -810.71  189.29
    2.00    2.00
 -810.59  189.41
Pier Skew, UpSta & Num, DnSta & Num=  ,10007.51, 2 ,10008.77, 2 , 0 , 0 , 0 ,,
    2.00    2.00
 -809.39  190.61
    2.00    2.00
 -809.27  190.73
BR Coef=-1 , 0 , 0 ,, 0 ,,,0.8,0,1,0,
WSPro=,,,, 1 ,,,, 0 ,,,, 0 ,,,,-1 ,-1 ,-1 , 0 , 0 , 0 , 0 , 0
BC Design=,, 0 ,, 0 ,,,,,,

Type RM Length L Ch R = 1 ,6879.535,284.688600,284.688600,284.688600
XS GIS Cut Line= 6
800822.768488736797957.745109764 800905.89381558797861.585646506
800967.643380667797753.012441055800996.920393826797647.208887992
801010.362247975797531.926656553801215.174796583797394.251831377
#Sta/Elev= 30
9449.552208.6075  9480.9210.26169533.454210.57649543.853209.33769559.588203.4237
9575.324200.51849584.674201.73639593.015204.22779596.736202.66959608.798192.1081
9699.769190.27799720.903190.76939741.938190.09659752.456191.34539773.195191.6277
9864.501190.57079945.712186.36769957.621186.0744 9969.53187.19439977.867183.5037
9981.438181.06349993.347176.173510017.16177.305610029.07187.649510040.98201.1281
10051.53 205.144 10064.8205.905610105.02211.377110125.76212.989610175.13214.1574
#Mann= 3 , 0 , 0
9449.552   0.058       09449.552   0.058       010175.13   0.058       0
#XS Ineff= 2 , 0
       09966.633         10056.1       0
Bank Sta=9449.552,10175.13
Exp/Cntr=0.3,0.1

Type RM Length L Ch R = 1 ,6594.846,197.898600,197.898600,197.898600
XS GIS Cut Line= 3
800901.082855523797934.652836636801003.947438866797791.423669949
801458.374522179797675.538253292
#Sta/Elev= 30
9606.335209.52359647.336211.08779655.154210.63119667.466205.2587 9692.09205.2805
9698.765201.21899704.401196.04119716.713191.06549741.336190.2992 9808.67189.7095
9825.041188.41629845.681184.83689897.281 183.5349938.562183.04119969.522185.2927
9979.842179.32429990.162175.055110000.48174.3723 10010.8175.513410031.44 180.612
10041.76181.274210052.08180.859210072.72184.903210103.68197.5803   10114200.2784
10124.32201.780610144.96203.228810155.28204.756910186.24206.660810251.65208.1167
#Mann= 3 , 0 , 0
9606.335    0.06       09606.335    0.06       010251.65    0.06       0
#XS Ineff= 2 , 0
       09913.045                       0
Bank Sta=9606.335,10251.65
Exp/Cntr=0.3,0.1

Type RM Length L Ch R = 1 ,6396.947,53.080400,53.080400,53.080400
XS GIS Cut Line= 5
800928.266447546797925.932253588800930.209644423797925.614897893
801104.172833995 797869.42802918801227.351738469797961.271949158
801533.137966142797921.292831064
#Sta/Elev= 30
9734.558211.52499771.064211.16149804.613208.80939815.122206.4759 9825.63201.8464
9836.139198.19769846.647198.60959857.156197.74599867.665193.57029878.173185.7928
9888.682183.65079945.318182.25389962.119179.29599978.849173.79569982.739 173.465
9995.213174.416210020.16174.206210029.04176.809110045.11184.1711 10062.5182.8948
10070.06183.022410110.96187.601710161.38188.231610181.55190.521510211.81192.0245
10242.06195.5527 10282.4198.051210302.57202.445310312.66203.540610381.38204.4443
#Mann= 3 , 0 , 0
9734.558  0.0697       09734.558  0.0697       010381.38  0.0697       0
#XS Ineff= 2 , 0
       09939.896        10060.75       0
Bank Sta=9734.558,10381.38
Exp/Cntr=0.3,0.1

Type RM Length L Ch R = 3 ,6376.781,,,
BEGIN DESCRIPTION:
END DESCRIPTION:
Bridge Culvert--1,0,-1,-1, 0
Deck Dist Width WeirC Skew NumUp NumDn MinLoCord MaxHiCord MaxSubmerge Is_Ogee
14.040200,25.000000,2.6,0, 54, 54, , , 0.95, 0, 0,0,,
 9809.94 9812.53 9823.02 9829.61 9833.51 9844.00 9854.49 9862.69 9864.98 9875.47
 9885.96 9895.78 9896.45 9906.94 9917.43 9926.40 9928.21 9940.66 9941.93 9942.66
 9942.66 9945.7310042.6610042.6610051.2710052.7610059.3510065.2210076.1210077.67
10078.3810089.3110089.6710099.5210109.6810119.8510129.2710130.0110140.1710150.33
10160.5010170.6610180.8210185.3910190.9810201.1510211.3110221.4710231.6310241.50
10241.8010251.9610262.1210263.03
  210.94  210.86  210.81  210.11  209.55  207.16  201.62  201.15  201.21  201.03
  197.58  191.39  190.95  183.80  183.13  182.79  182.67  182.02  181.97  181.83
  181.83  181.24  181.49  181.49  181.52  181.66  181.85  182.08  182.09  182.11
  182.18  182.70  182.71  183.44  184.16  185.32  186.90  187.02  187.66  187.81
  188.01  188.54  189.86  190.02  190.19  190.77  191.24  191.56  191.52  192.02
  192.04  193.69  195.19  195.28
 -789.06 -789.14 -789.19 -789.89 -790.45 -792.84 -798.38 -798.85 -798.79 -798.97
 -802.42 -808.61 -809.05 -816.20 -816.87 -817.21 -817.33 -817.98 -818.03 -818.17
  179.33  178.74  178.99 -818.51 -818.48 -818.34 -818.15 -817.92 -817.91 -817.89
 -817.82 -817.30 -817.29 -816.56 -815.84 -814.68 -813.10 -812.98 -812.34 -812.19
 -811.99 -811.46 -810.14 -809.98 -809.81 -809.23 -808.76 -808.44 -808.48 -807.98
 -807.96 -806.31 -804.81 -804.72
 9809.94 9812.53 9823.02 9829.61 9833.51 9844.00 9854.49 9862.69 9864.98 9875.47
 9885.96 9895.78 9896.45 9906.94 9917.43 9926.40 9928.21 9940.66 9941.93 9945.73
 9948.01 9948.0110048.0110048.0110051.2710052.7610059.3510065.2210076.1210077.67
10078.3810089.3110089.6710099.5210109.6810119.8510129.2710130.0110140.1710150.33
10160.5010170.6610180.8210185.3910190.9810201.1510211.3110221.4710231.6310241.50
10241.8010251.9610262.1210263.03
  210.94  210.86  210.81  210.11  209.55  207.16  201.62  201.15  201.21  201.03
  197.58  191.39  190.95  183.80  183.13  182.79  182.67  182.02  181.97  181.24
  181.25  181.25  181.51  181.51  181.52  181.66  181.85  182.08  182.09  182.11
  182.18  182.70  182.71  183.44  184.16  185.32  186.90  187.02  187.66  187.81
  188.01  188.54  189.86  190.02  190.19  190.77  191.24  191.56  191.52  192.02
  192.04  193.69  195.19  195.28
 -789.06 -789.14 -789.19 -789.89 -790.45 -792.84 -798.38 -798.85 -798.79 -798.97
 -802.42 -808.61 -809.05 -816.20 -816.87 -817.21 -817.33 -817.98 -818.03 -818.76
 -818.75  178.75  179.01 -818.49 -818.48 -818.34 -818.15 -817.92 -817.91 -817.89
 -817.82 -817.30 -817.29 -816.56 -815.84 -814.68 -813.10 -812.98 -812.34 -812.19
 -811.99 -811.46 -810.14 -809.98 -809.81 -809.23 -808.76 -808.44 -808.48 -807.98
 -807.96 -806.31 -804.81 -804.72
Pier Skew, UpSta & Num, DnSta & Num=  ,9956.23, 2 ,9961.59, 2 , 0 , 0 , 0 ,,
    2.00    2.00
 -818.73  181.27
    2.00    2.00
 -818.72  181.28
Pier Skew, UpSta & Num, DnSta & Num=  ,9970.80, 2 ,9976.16, 2 , 0 , 0 , 0 ,,
    2.00    2.00
 -818.69  181.31
    2.00    2.00
 -818.68  181.32
Pier Skew, UpSta & Num, DnSta & Num=  ,9985.37, 2 ,9990.73, 2 , 0 , 0 , 0 ,,
    2.00    2.00
 -818.65  181.35
    2.00    2.00
 -818.64  181.36
Pier Skew, UpSta & Num, DnSta & Num=  ,9999.95, 2 ,10005.30, 2 , 0 , 0 , 0 ,,
    2.00    2.00
 -818.62  181.38
    2.00    2.00
 -818.60  181.40
Pier Skew, UpSta & Num, DnSta & Num=  ,10014.52, 2 ,10019.87, 2 , 0 , 0 , 0 ,,
    2.00    2.00
 -818.58  181.42
    2.00    2.00
 -818.57  181.43
Pier Skew, UpSta & Num, DnSta & Num=  ,10029.09, 2 ,10034.44, 2 , 0 , 0 , 0 ,,
    2.00    2.00
 -818.54  181.46
    2.00    2.00
 -818.53  181.47
BR Coef=-1 , 0 , 0 ,, 0 ,,,0.8,0,1,0,
WSPro=,,,, 1 ,,,, 0 ,,,, 0 ,,,,-1 ,-1 ,-1 , 0 , 0 , 0 , 0 , 0
BC Design=,, 0 ,, 0 ,,,,,,

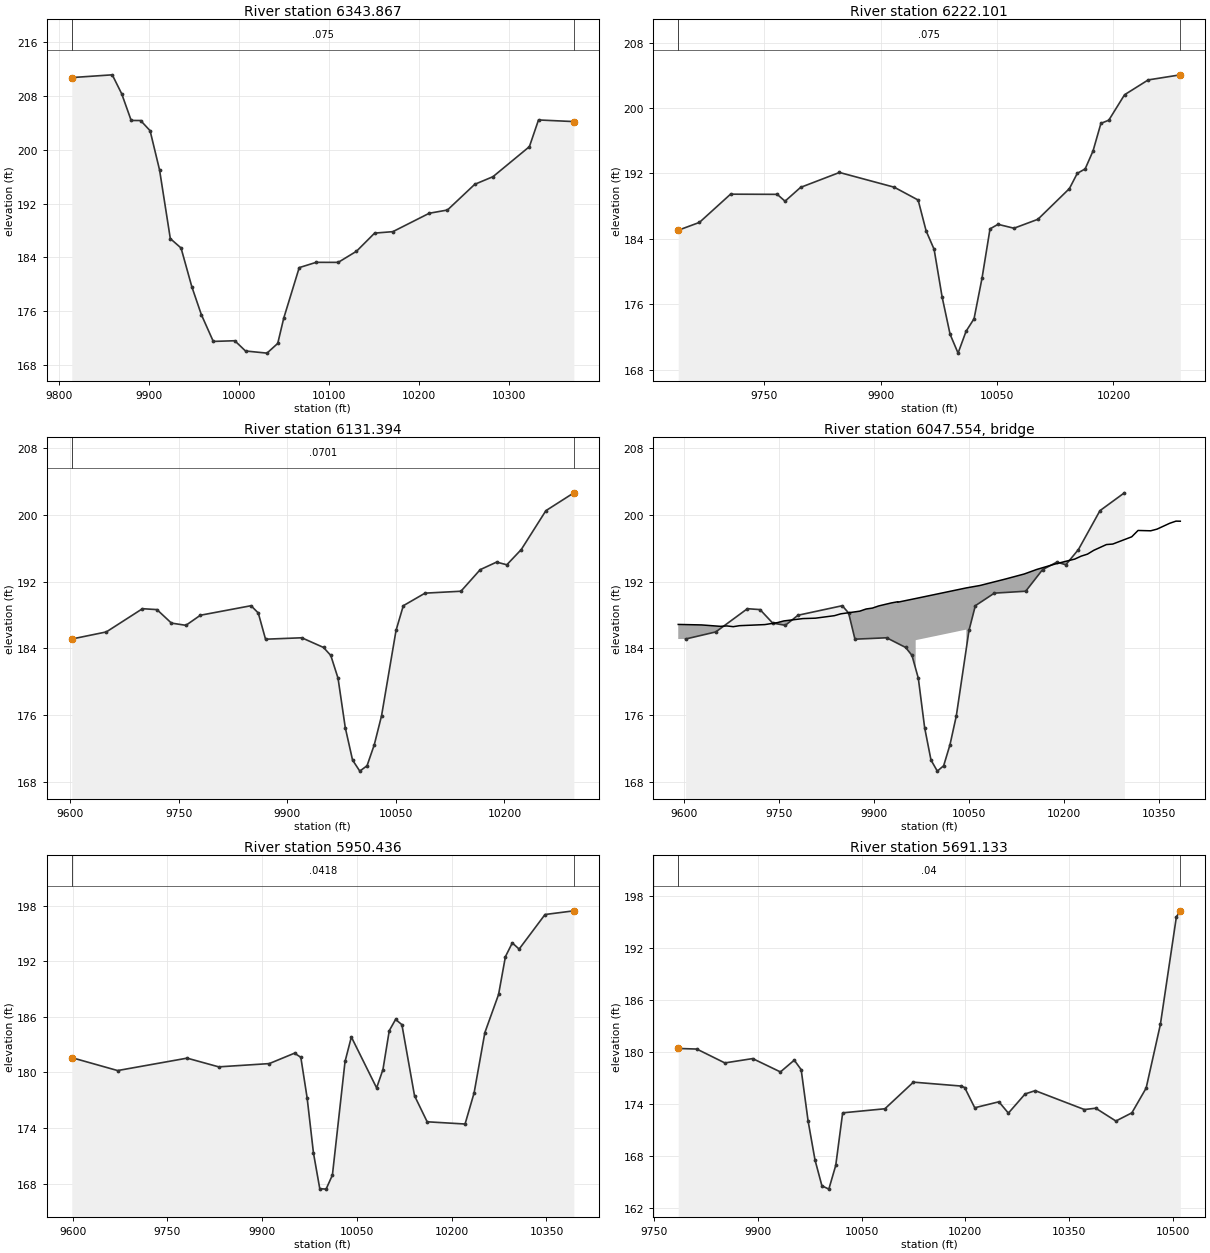
Type RM Length L Ch R = 1 ,6343.867,121.765900,121.765900,121.765900
XS GIS Cut Line= 4
800972.179698978797939.508448672801064.858778126 797909.57483303
801210.728533424 798004.66030311801493.823910302797961.439634914
#Sta/Elev= 30
 9813.77  210.769858.768211.16969869.277208.33869879.785204.37519890.294204.3648
9900.803202.84769911.331196.99829923.268186.78659935.205185.38329947.142179.6304
9957.722175.47639971.016171.4767 9994.89171.577210006.83170.0522 10030.7169.7332
10042.64171.181210049.28174.930210066.51182.463610085.29  183.2510109.84183.2472
10130.07 184.894 10150.3 187.60410170.53187.8181   10211190.558410231.23191.0423
10261.58194.871110281.81196.004310322.27200.475510332.39204.451410371.66204.2071
#Mann= 3 , 0 , 0
 9813.77   0.075       0 9813.77   0.075       010371.66   0.075       0
#XS Ineff= 2 , 0
       09929.973        10068.97       0
Bank Sta=9813.77,10371.66
Exp/Cntr=0.3,0.1

Type RM Length L Ch R = 1 ,6222.101,90.707000,90.707000,90.707000
XS GIS Cut Line= 4
800817.749522179798076.579919949801083.374522179798096.111169964
801270.874522179798050.538253292801455.770355523798017.986169964
#Sta/Elev= 30
9639.183 185.0569666.507186.01499706.615189.46399766.777189.44349776.804188.6054
9796.858190.29439846.993192.11679917.489190.31719948.363188.74689958.654184.9736
9968.945 182.7229979.236176.90879989.527 172.3419999.818170.038210010.11172.7075
 10020.4174.239710030.69179.202710040.98185.221610051.27185.778810071.86185.3022
10102.67 186.39310143.29190.147510153.44192.0092 10163.6192.553810173.75194.7476
 10183.9 198.11610194.06198.506910214.36201.614310244.83203.427410286.22204.0496
#Mann= 3 , 0 , 0
9639.183   0.075       09639.183   0.075       010286.22   0.075       0
#XS Ineff= 2 , 0
       09942.441                       0
Bank Sta=9639.183,10286.22
Exp/Cntr=0.3,0.1

Type RM Length L Ch R = 1 ,6131.394,180.957900,180.957900,180.957900
XS GIS Cut Line= 4
  800807.2922368798144.097442394801056.898827732798149.496586621
801319.485633314 798166.85769774801479.037592823798081.172386154
#Sta/Elev= 30
9601.959185.11989649.678 185.969 9699.69188.75689719.695188.64799739.699187.0296
9759.704 186.7639779.709187.97149849.725189.11469859.743188.24099869.765185.0979
9919.874185.2689 9949.94184.10669959.961183.14859969.983180.41589980.005174.4778
9990.027170.606410000.05169.274410010.07169.921510020.09172.445510030.11175.9134
10050.16186.161510060.18189.114410090.25190.622210139.85190.851310166.45193.4384
10189.15194.348510203.25194.0239 10223.2 195.85110257.25200.515310295.89202.6547
#Mann= 3 , 0 , 0
9601.959  0.0701       09601.959  0.0701       010295.89  0.0701       0
#XS Ineff= 2 , 0
       09934.888        10071.28       0
Bank Sta=9601.959,10295.89
Exp/Cntr=0.3,0.1

Type RM Length L Ch R = 3 ,6047.554,,,
BEGIN DESCRIPTION:
END DESCRIPTION:
Bridge Culvert--1,0,-1,-1, 0
Deck Dist Width WeirC Skew NumUp NumDn MinLoCord MaxHiCord MaxSubmerge Is_Ogee
56.478950,68.000000,2.6,0, 42, 40, , , 0.95, 0, 0,0,,
 9590.30 9627.22 9657.23 9667.24 9677.24 9687.25 9727.27 9747.28 9757.29 9787.30
 9807.31 9837.33 9847.33 9877.35 9887.35 9897.36 9907.36 9927.37 9937.38 9937.70
 9965.86 9965.8610045.8610045.8610067.4510107.4710137.4910157.4910187.4910217.49
10227.4910237.4910247.4910267.4910277.4910307.4910317.4910337.4910347.4910367.49
10377.4910384.33
  186.87  186.81  186.64  186.69  186.60  186.72  186.85  187.09  187.29  187.57
  187.62  187.92  188.14  188.46  188.72  188.83  189.09  189.45  189.59  189.54
  189.98  189.98  191.25  191.25  191.54  192.31  192.92  193.47  194.14  194.71
  195.06  195.30  195.76  196.45  196.51  197.38  198.14  198.10  198.30  199.00
  199.26  199.25
 -813.13 -813.19 -813.36 -813.31 -813.40 -813.28 -813.15 -812.91 -812.71 -812.43
 -812.38 -812.08 -811.86 -811.54 -811.28 -811.17 -810.91 -810.55 -810.41 -810.46
 -810.02  184.98  186.25 -808.75 -808.46 -807.69 -807.08 -806.53 -805.86 -805.29
 -804.94 -804.70 -804.24 -803.55 -803.49 -802.62 -801.86 -801.90 -801.70 -801.00
 -800.74 -800.75
 9590.30 9627.22 9657.23 9667.24 9677.24 9687.25 9727.27 9747.28 9757.29 9787.30
 9807.31 9837.33 9847.33 9877.35 9887.35 9897.36 9907.36 9927.37 9954.03 9954.03
10034.0310034.0310067.4510087.4610137.4910157.4910187.4910217.4910227.4910237.49
10247.4910267.4910277.4910307.4910317.4910337.4910347.4910367.4910377.4910384.33
  186.87  186.81  186.64  186.69  186.60  186.72  186.85  187.09  187.29  187.57
  187.62  187.92  188.14  188.46  188.72  188.83  189.09  189.45  189.80  189.80
  191.06  191.06  191.54  191.91  192.92  193.47  194.14  194.71  195.06  195.30
  195.76  196.45  196.51  197.38  198.14  198.10  198.30  199.00  199.26  199.25
 -813.13 -813.19 -813.36 -813.31 -813.40 -813.28 -813.15 -812.91 -812.71 -812.43
 -812.38 -812.08 -811.86 -811.54 -811.28 -811.17 -810.91 -810.55 -810.20  184.80
  186.06 -808.94 -808.46 -808.09 -807.08 -806.53 -805.86 -805.29 -804.94 -804.70
 -804.24 -803.55 -803.49 -802.62 -801.86 -801.90 -801.70 -801.00 -800.74 -800.75
BR Coef=-1 , 0 , 0 ,, 0 ,,,0.8,0,1,0,
WSPro=,,,, 1 ,,,, 0 ,,,, 0 ,,,,-1 ,-1 ,-1 , 0 , 0 , 0 , 0 , 0
BC Design=,, 0 ,, 0 ,,,,,,

Type RM Length L Ch R = 1 ,5950.436,259.302800,259.302800,259.302800
XS GIS Cut Line= 4
800822.400538743798341.540845826801367.419460952798338.024594709
801459.316808462798338.625784844801604.800268412798277.265413955
#Sta/Elev= 30
9598.519181.5967 9671.12180.20469781.123181.54349831.124180.60369911.125180.9546
9951.126182.07769961.126181.63569971.127177.25199981.127171.32069991.127167.4686
10001.13167.420210011.13168.935110031.13181.182210041.13183.824510081.13178.3323
10091.13180.311910101.13184.503210111.13185.718310121.13185.154110141.13 177.489
10161.13174.681810221.13174.440810235.45177.799810252.47184.297110274.18188.4093
10285.03192.487410295.88193.967710306.74193.302610347.71197.030210393.34197.4276
#Mann= 3 , 0 , 0
9598.519  0.0418       09598.519  0.0418       010393.34  0.0418       0
#XS Ineff= 2 , 0
       09936.823        10058.83       0
Bank Sta=9598.519,10393.34
Exp/Cntr=0.3,0.1

Type RM Length L Ch R = 1 ,5691.133,261.517600,261.517600,261.517600
XS GIS Cut Line= 6
801018.747469842798618.403270692801096.083172321798604.344501838
801149.585039288798599.283848971801277.867029339798598.440960601
801312.211400181 798596.73157692801625.976017922798301.102792904
#Sta/Elev= 30
9784.891180.36739811.783180.2978  9852.3 178.6999892.572179.19979932.689 177.661
  9952.7179.01859962.705177.92259972.707172.00599982.707167.50939992.708164.5299
10002.71164.147610012.71 166.88810022.71172.9435 10083.8173.413410125.01176.4825
10193.71176.034810199.15175.864810213.73173.530710248.67174.218310262.41172.9107
10286.64175.125410301.22175.501210372.32173.323910388.72173.477210417.88172.0006
10441.02172.945910461.63175.795710482.24183.138410505.38195.541810511.06196.2365
#Mann= 3 , 0 , 0
9784.891    0.04       09784.891    0.04       010511.06    0.04       0
#XS Ineff= 2 , 0
       0                10055.78       0
Bank Sta=9784.891,10511.06
Exp/Cntr=0.3,0.1

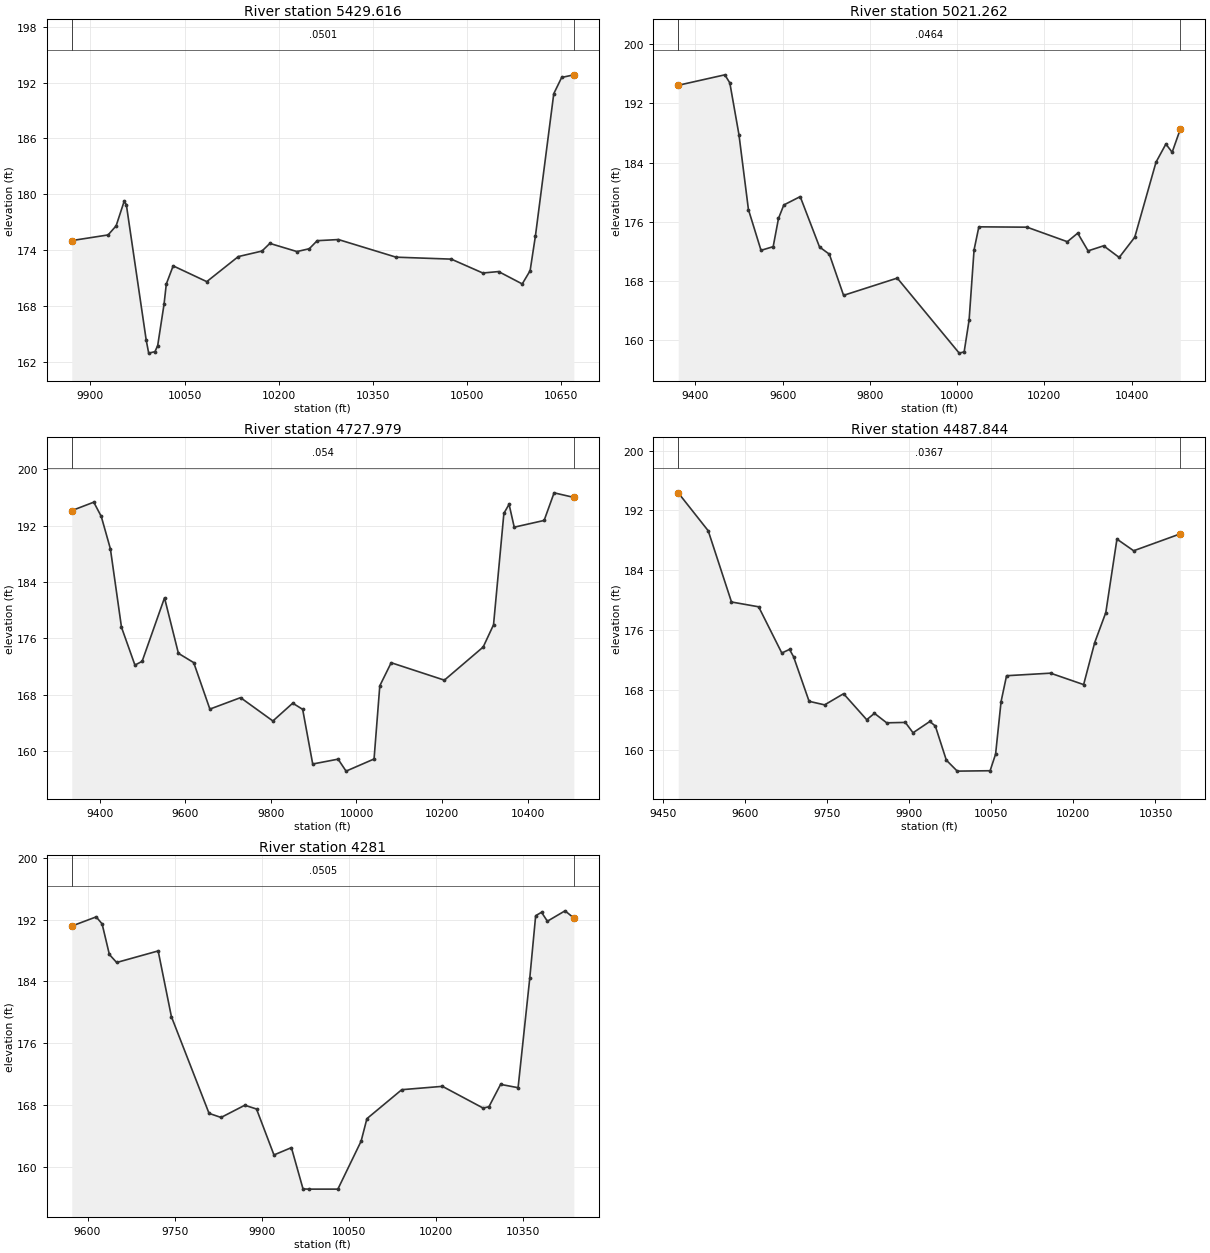
Type RM Length L Ch R = 1 ,5429.616,408.353300,408.353300,408.353300
XS GIS Cut Line= 6
 801210.95086655798940.345277861801283.098259687798849.471668065
801296.956143409798836.203925088801322.154196709798809.461299807
801341.861536086798783.110266179801702.024968982798309.552676365
#Sta/Elev= 30
9870.201  175.049928.099175.64749940.868176.62339953.636179.25229957.125178.9012
9988.821164.34269992.736162.9606 10002.7163.115810007.07163.769510017.15168.1828
10020.81170.380210031.73172.326710085.26170.633910135.51173.3239 10173.2173.9155
10185.76174.737610228.92173.861610248.58174.166310261.15175.0298   10295175.1512
10386.78173.259710474.73173.050310524.98171.560810550.11171.7147 10587.8170.3872
10600.36171.809110608.86175.556310638.05190.810110650.62  192.5510670.02192.8312
#Mann= 3 , 0 , 0
9870.201  0.0501       09870.201  0.0501       010670.02  0.0501       0
#XS Ineff= 2 , 0
       0                10085.42       0
Bank Sta=9870.201,10670.02
Exp/Cntr=0.3,0.1

Type RM Length L Ch R = 1 ,5021.262,293.283400,293.283400,293.283400
XS GIS Cut Line= 6
801456.558416992799275.990650088801611.262542605799075.965240613
801676.089821488798951.753777921801688.969283432798833.123655692
801585.457806677798587.573232666801785.115489542798277.161456481
#Sta/Elev= 30
9360.646194.4444 9467.52195.85689478.908194.76659499.828187.78299521.591177.6525
9550.437172.14319578.301172.63989590.502176.45559602.704178.27219640.251179.4015
9684.611172.59219707.036171.62669739.688166.06259862.757168.392110004.79158.2551
10016.14158.426610027.49162.727110038.84172.201910049.85175.318910160.25 175.272
10252.68173.309910276.46174.463610300.24 172.07110335.91172.755910371.58171.1819
10407.25 173.91810456.02184.057310478.59186.503810492.99185.397910511.69188.5212
#Mann= 3 , 0 , 0
9360.646  0.0464       09360.646  0.0464       010511.69  0.0464       0
#XS Ineff= 2 , 0
       0                10050.48       0
Bank Sta=9360.646,10511.69
Exp/Cntr=0.3,0.1

Type RM Length L Ch R = 1 ,4727.979,240.135400,240.135400,240.135400
XS GIS Cut Line= 6
801500.661927731 799284.31710406 801682.60022461799047.586961135
 801790.62749191798843.659125207801840.584775384 798773.19032363
802071.702741131798574.183780539802285.167904887798439.896544446
#Sta/Elev= 30
  9334.2194.11419385.657195.30959403.194193.28439424.542188.68629450.465177.5679
9481.909172.19459498.754172.73089551.099181.73799583.607 173.8649619.415172.5449
9657.176165.95219728.905 167.5799804.579164.2678 9850.95166.79319874.175 165.918
9897.683158.16079957.001158.85159975.704157.151910041.15158.874510054.56169.2573
10081.18172.532210205.58170.058410296.33174.758710320.55 177.91710344.77193.7253
10356.87195.014610368.95191.763110438.88192.719410462.19196.636710508.37195.9865
#Mann= 3 , 0 , 0
  9334.2   0.054       0  9334.2   0.054       010508.37   0.054       0
#XS Ineff= 2 , 0
       0                               0
Bank Sta=9334.2,10508.37
Exp/Cntr=0.3,0.1

Type RM Length L Ch R = 1 ,4487.844,206.843700,206.843700,206.843700
XS GIS Cut Line= 6
801540.839799941799273.628531069801846.286726601798969.775056082
802031.917840347798960.156238795802128.553434512798950.210704495
802259.154220785798927.682916675802328.083958312798911.298183308
#Sta/Elev= 30
9478.009194.34939532.782189.27829575.319179.7587 9624.93179.11539667.246172.9383
9681.351173.42229688.754172.43819717.112166.48459745.471166.00749780.088167.4982
9822.404 164.023 9836.51164.87629858.905163.60819892.931163.66429907.036162.2771
9937.712163.78969947.763163.17979967.824158.62269987.832157.151910047.87157.2055
10057.88159.434110067.88166.449210077.89 169.90410158.23170.245810218.71168.7177
10238.94174.330310259.23178.344610279.58188.163710310.11186.606910395.36188.8678
#Mann= 3 , 0 , 0
9478.009  0.0367       09478.009  0.0367       010395.36  0.0367       0
#XS Ineff= 2 , 0
       0                               0
Bank Sta=9478.009,10395.36
Exp/Cntr=0.3,0.1

Type RM Length L Ch R = 1 ,    4281,0.000000,0.000000,0.000000
XS GIS Cut Line= 6
801534.345435409799311.678819204801680.926037665799210.837890301
801783.406986683799177.984007759801895.188045201799169.746962181
802184.330124849799172.716975134802359.892785499799151.179420061
#Sta/Elev= 30
9572.826191.15429614.898192.34169625.081191.43379637.591187.4821  9650.1186.4461
9721.624187.94029744.454179.44219809.285166.94319829.946166.41639870.836167.9962
9891.027167.50749921.082161.56899951.112162.51619971.132157.17819981.132157.1519
10031.15157.151910071.16163.349810081.17166.260810141.19170.004310211.22170.4377
 10281.3167.629610291.34 167.80310311.41170.691210341.52170.261810361.71184.4614
10371.81192.4946 10381.9192.9349   10392191.780610422.41193.123810437.57192.1944
#Mann= 3 , 0 , 0
9572.826  0.0505       09572.826  0.0505       010437.57  0.0505       0
#XS Ineff= 2 , 0
       0                               0
Bank Sta=9572.826,10437.57
Exp/Cntr=0.3,0.1